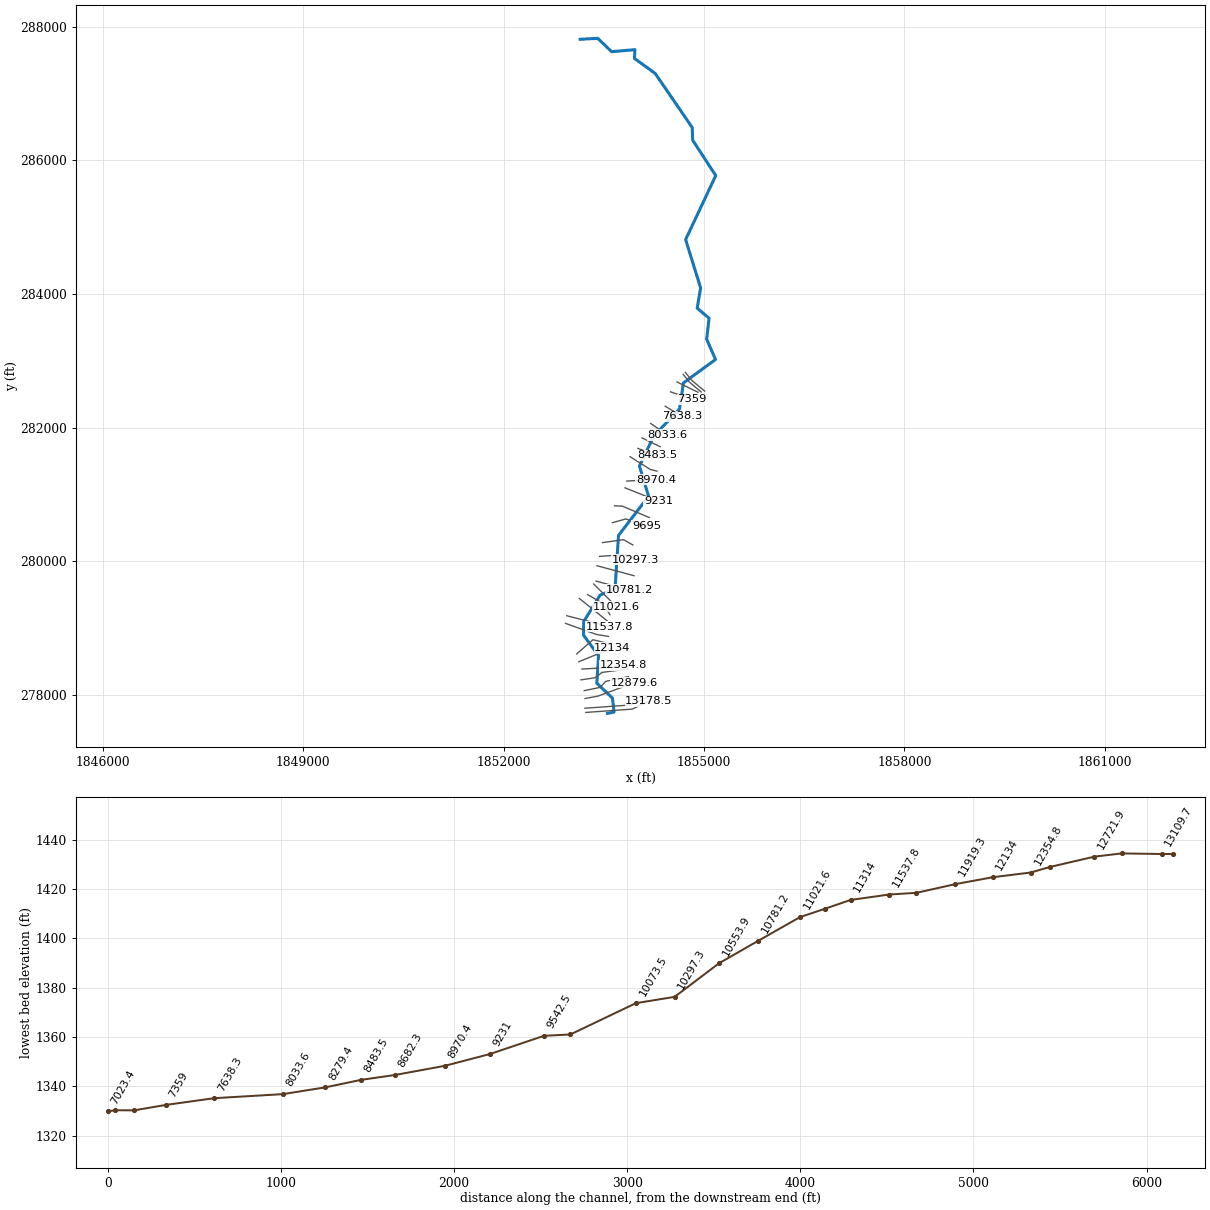
--- LCOVERN.prj (project) ---

Proj Title=LCOVERN
Current Plan=p01
Default Exp/Contr=0,0
English Units
Geom File=g01
Flow File=f01
Plan File=p01
BEGIN DESCRIPTION:
END DESCRIPTION:
DSS Export Rating Curves= 0
DSS Export Rating Curve Sorted= 0
DSS Export Volume Flow Curves= 0
DXF OffsetX= 0
DXF OffsetY= 0
DXF ScaleX= 0
DXF ScaleY= 0

--- LCOVERN.p01 (plan) ---

Plan Title=Floodplain
Program Version=4.00
Geom File=g01
Flow File=f01
K Sum by GR=0
Std Step Tol=0.01
Critical Tol=0.01
Num of Std Step Trials=20
Max Error Tol=0.3
Flow Tol Ratio=0.001
Split Flow NTrial=30
Split Flow Tol=0.02
Split Flow Ratio=0.02
Log Output Level=0
Friction Slope Method=1
Unsteady Friction Slope Method=2
Unsteady Bridges Friction Slope Method=1
Global Log Level=0
CheckData=False
Run HTab=0
Run UNet=0
Run PostProcess=0
UNET Theta=0
UNET Theta Warmup=0
UNET ZTol=0
UNET ZSATol=0
UNET MxIter=0
UNET MaxInSteps=0
UNET DtIC=0
UNET DtMin=0
UNET MaxCRTS=0
UNET WFStab=0
UNET SFStab=0
UNET WFX=0
UNET SFX=0
UNET DSS MLevel=0
UNET DZMax Abort=0
UNET Convert EG Bridges=0
UNET Use Existing IB Tables=0
UNET Froude Limit=0
UNET Froude Power=0
Write IC File=0
Echo Input=False
Echo Output=False
Write Detailed=0

--- LCOVERN.f01 (steady flow) ---

Flow Title=NFF Regression Equation
Program Version=4.00
Number of Profiles=1
Profile Names=P100yr
River Rch & RM=LCOVERN,Main      ,13178.5
518.9471
River Rch & RM=LCOVERN,Main      ,11537.8
535.5381
River Rch & RM=LCOVERN,Main      ,11314
594.5166
River Rch & RM=LCOVERN,Main      ,10297.3
647.0433
River Rch & RM=LCOVERN,Main      ,6742.4
716.1581
River Rch & RM=LCOVERN,Main      ,6151.9
852.7676
River Rch & RM=LCOVERN,Main      ,2346.1
927.1387
River Rch & RM=LCOVERN,Main      ,595.6
1028.953
River Rch & RM=LCOVERN,Main      ,242.1
1030.276
Boundary for River Rch & Prof#=LCOVERN,Main      ,1
Up Type=0
Dn Type=3
Dn Slope=0.008267

--- LCOVERN.g01 (geometry) ---

Geom Title=USGS 10m DEM
Program Version=4.10

River Reach=LCOVERN         ,Main
Reach XY= 30
     1853553.789      277721.226      1853652.83        277739.8
     1853627.786      277950.367     1853394.763      278171.984
     1853420.297      278586.427     1853195.859      278890.779
      1853197.18      279094.189      1853443.85       279492.29
     1853667.093      279586.134     1853719.176      280385.606
     1854169.163      280971.328     1854032.433      281424.444
     1854246.949      281874.308     1854632.646      282278.476
     1854691.389      282668.572     1855171.764      283019.723
     1855038.604         283323.     1855075.381      283637.195
      1854896.97       283788.07     1854948.787      284090.717
     1854723.853      284814.406     1855174.892       285772.71
     1854829.487      286302.886     1854822.601      286492.299
     1854267.615      287303.127     1853958.621      287525.907
     1853963.693      287658.064       1853616.1       287627.51
     1853408.554       287827.68     1853144.726      287813.147

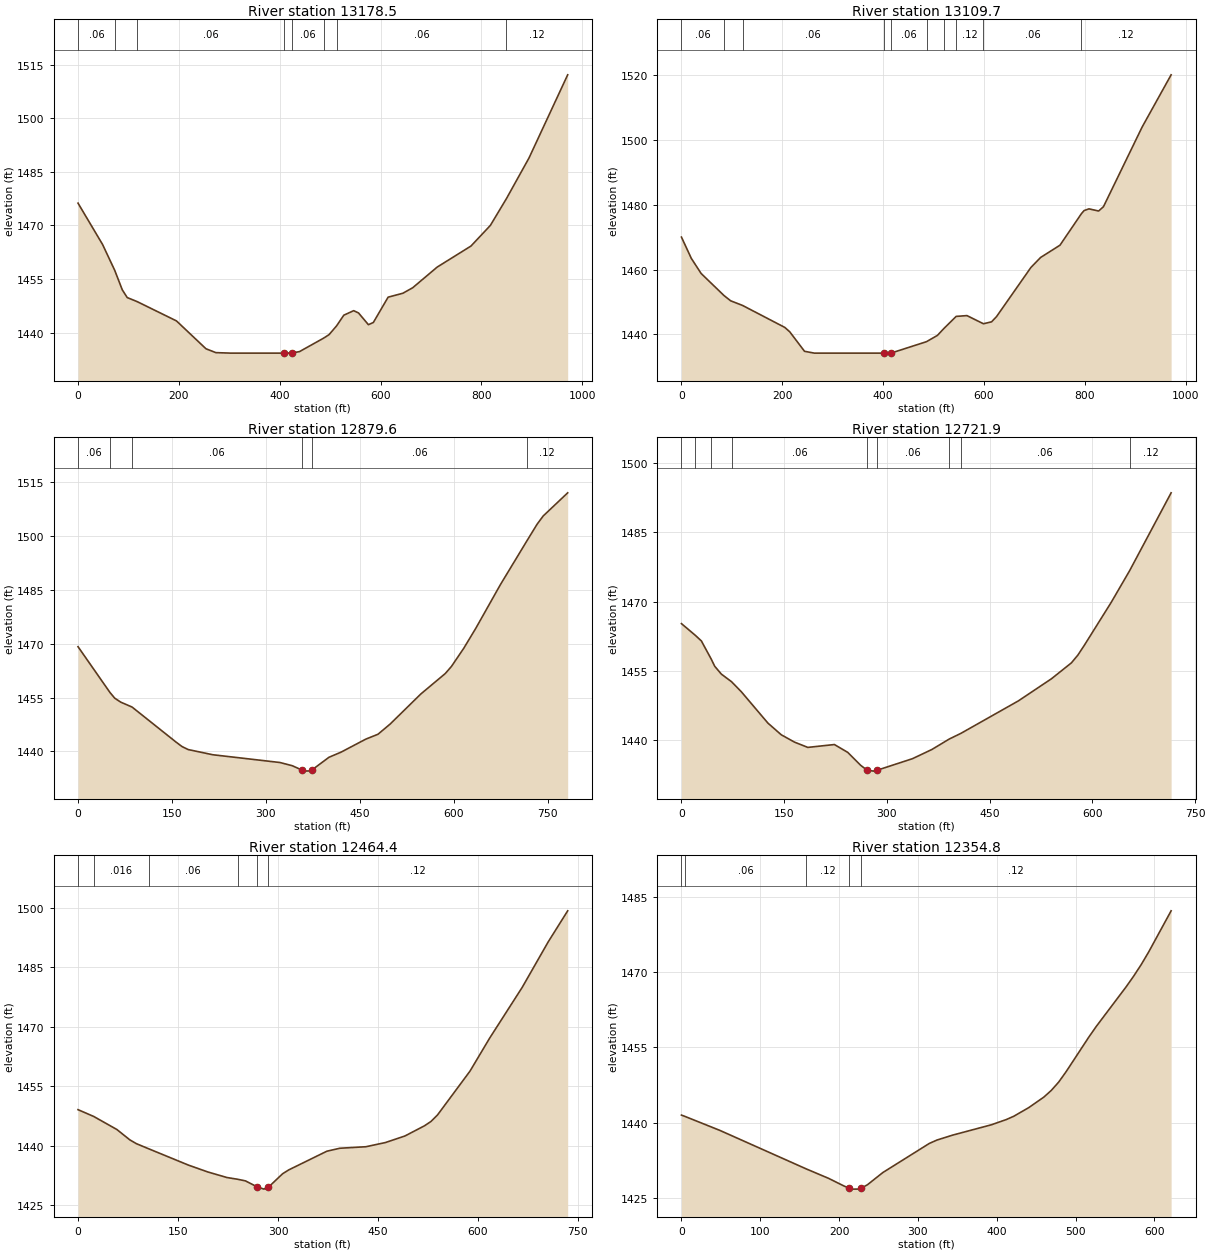
Type RM Length L Ch R = 1 ,13178.5 ,66.8,68.8,68.9
XS GIS Cut Line= 3
     1853230.286      277735.401     1853921.729      277784.712
     1854174.519       277900.73
#Sta/Elev= 30
       0 1476.26    48.8 1464.66   72.771457.454    87.9 1451.96    97.6 1449.82
  117.421448.676   195.3 1443.28   253.8 1435.48   273.4  1434.4   302.7 1434.26
   409.2 1434.26   424.2 1434.29   439.4 1434.69  487.081438.451   497.9 1439.43
  512.76 1441.87   527.2 1444.88   546.8 1446.15   556.5  1445.5     576 1442.22
   585.8 1442.84   615.1 1449.93   644.4 1451.03   663.9 1452.57   712.4 1458.35
   779.5 1464.25   817.9 1470.02   849.91477.545   894.6 1488.91   971.3 1512.19
#Mann= 8 ,-1 , 0
       0     .06       0   72.77    .016       0  117.42     .06       0
   409.2    .045       0   424.2     .06       0  487.08     .12       0
  512.76     .06       0   849.9     .12       0
Bank Sta=409.2,424.2
XS Rating Curve= 0 ,0
Exp/Cntr=0.3,0.1

Type RM Length L Ch R = 1 ,13109.7 ,223,230.1,236.3
XS GIS Cut Line= 3
     1853215.095      277798.335     1853906.538      277847.646
     1854159.328      277963.664
#Sta/Elev= 30
       0    1470    19.5 1463.46      39  1458.8    84.4    1452    97.6 1450.38
  121.331448.941     205 1442.18   214.8 1440.83   244.1 1434.82   263.6 1434.26
   401.6 1434.26   416.6 1434.32  486.071437.789   507.7 1439.72  521.081441.931
  544.931445.578   566.3 1445.82     5991443.308   615.1  1443.9   624.9  1445.5
   693.2 1460.66   712.4 1463.73   750.8 1467.51  793.361477.229   798.7 1478.18
   808.3 1478.71   827.5 1478.04   837.1 1479.38   913.8 1503.92   971.3    1520
#Mann= 10 ,-1 , 0
       0     .06       0    84.4    .016       0  121.33     .06       0
   401.6    .045       0   416.6     .06       0  486.07     .12       0
  521.08     .06       0  544.93     .12       0     599     .06       0
  793.36     .12       0
Bank Sta=401.6,416.6
XS Rating Curve= 0 ,0
Exp/Cntr=0.3,0.1

Type RM Length L Ch R = 1 ,12879.6 ,146.7,157.7,168.4
XS GIS Cut Line= 3
     1853218.108      277943.656     1853410.294      277979.655
     1853961.164      278181.503
#Sta/Elev= 30
       0 1469.18   51.021456.419    58.7 1454.82    68.4 1453.71    86.31452.363
   156.4 1442.62   166.2 1441.34     176 1440.51   215.1 1439.07   322.6  1436.9
   342.2 1436.01   357.6 1434.81   361.8  1434.5   371.5 1434.58  373.831434.853
   400.9 1438.36   420.4 1439.81   459.5  1443.4   479.1 1444.77   498.6 1447.62
   547.5 1455.98   586.6 1461.69   596.4 1463.65     616 1468.69   635.5 1474.33
   674.6 1486.44  716.961498.649   733.3  1503.3   743.1 1505.61   782.2 1512.06
#Mann= 6 ,-1 , 0
       0     .06       0   51.02    .016       0    86.3     .06       0
   357.6    .045       0  373.83     .06       0  716.96     .12       0
Bank Sta=357.6,373.83
XS Rating Curve= 0 ,0
Exp/Cntr=0.3,0.1

Type RM Length L Ch R = 1 ,12721.9 ,257.7,257.6,253
XS GIS Cut Line= 4
     1853205.955      278061.711     1853443.803      278110.322
     1853527.136        278200.6      1853869.15      278271.781
#Sta/Elev= 30
       0  1465.2   20.291462.657    29.1 1461.44   43.47  1457.5    48.6 1455.94
    58.3 1454.24   73.061452.603    87.4 1450.42   126.2 1443.62   145.7 1441.08
   165.1 1439.48   184.5 1438.34   223.3 1438.96   242.8 1437.26   261.7 1434.45
   271.1  1433.4   280.6 1433.19  285.931433.397   337.3 1435.89   365.6 1437.88
  391.051440.158  407.911441.377   491.8 1448.42   540.3 1453.24   569.4 1456.69
   579.1 1458.43   588.8 1460.63   627.6 1469.84  654.471476.713     715 1493.59
#Mann= 9 ,-1 , 0
       0     .06       0   20.29     .08       0   43.47    .016       0
   73.06     .06       0   271.1    .045       0  285.93     .06       0
  391.05     .12       0  407.91     .06       0  654.47     .12       0
Bank Sta=271.1,285.93
XS Rating Curve= 0 ,0
Exp/Cntr=0.3,0.1

Type RM Length L Ch R = 1 ,12464.4 ,123.5,109.6,95.8
XS GIS Cut Line= 4
     1853157.344      278223.169      1853369.15      278254.419
      1853471.58      278334.281     1853858.733      278386.364
#Sta/Elev= 30
       0 1449.05   23.531447.335    58.4 1444.03    77.8 1441.42    87.6 1440.46
   106.51439.142   165.4 1435.07   194.6 1433.33   223.4 1431.92  239.381431.482
   251.2 1431.07   269.11429.534     279 1428.99  284.331429.508   288.3  1429.9
   306.9 1432.87   316.2 1433.85   373.3 1438.56   392.8 1439.31   431.9 1439.69
   461.2 1440.75   490.5 1442.41   519.8 1444.98   529.5 1446.07   539.3 1447.71
   588.1 1458.79   617.4 1467.07   666.3  1479.9   705.3 1491.38   734.6 1499.24
#Mann= 6 ,-1 , 0
       0     .12       0   23.53    .016       0   106.5     .06       0
  239.38     .12       0   269.1    .045       0  284.33     .12       0
Bank Sta=269.1,284.33
XS Rating Curve= 0 ,0
Exp/Cntr=0.3,0.1

Type RM Length L Ch R = 1 ,12354.8 ,212.9,220.8,228.2
XS GIS Cut Line= 3
     1853171.233      278384.628     1853563.594      278407.197
     1853789.289      278440.183
#Sta/Elev= 30
       0 1441.49    4.261441.242    49.1 1438.42  158.571430.756   186.7 1428.89
   206.3 1427.36  213.041426.947   216.2 1426.75     226 1426.76  227.961426.932
   235.8 1427.61   255.5 1430.06   314.4 1435.85   324.2 1436.53   343.9  1437.5
     393 1439.56     412  1440.6   421.5 1441.26   440.5 1442.98   459.5 1445.06
     469 1446.39   478.5 1448.07     488 1450.16   516.6    1457   526.1 1459.14
   564.1 1467.05   573.6 1469.17   583.1 1471.45   592.6 1473.97   621.1 1482.17
#Mann= 5 ,-1 , 0
       0    .016       0    4.26     .06       0  158.57     .12       0
  213.04    .045       0  227.96     .12       0
Bank Sta=213.04,227.96
XS Rating Curve= 0 ,0
Exp/Cntr=0.3,0.1

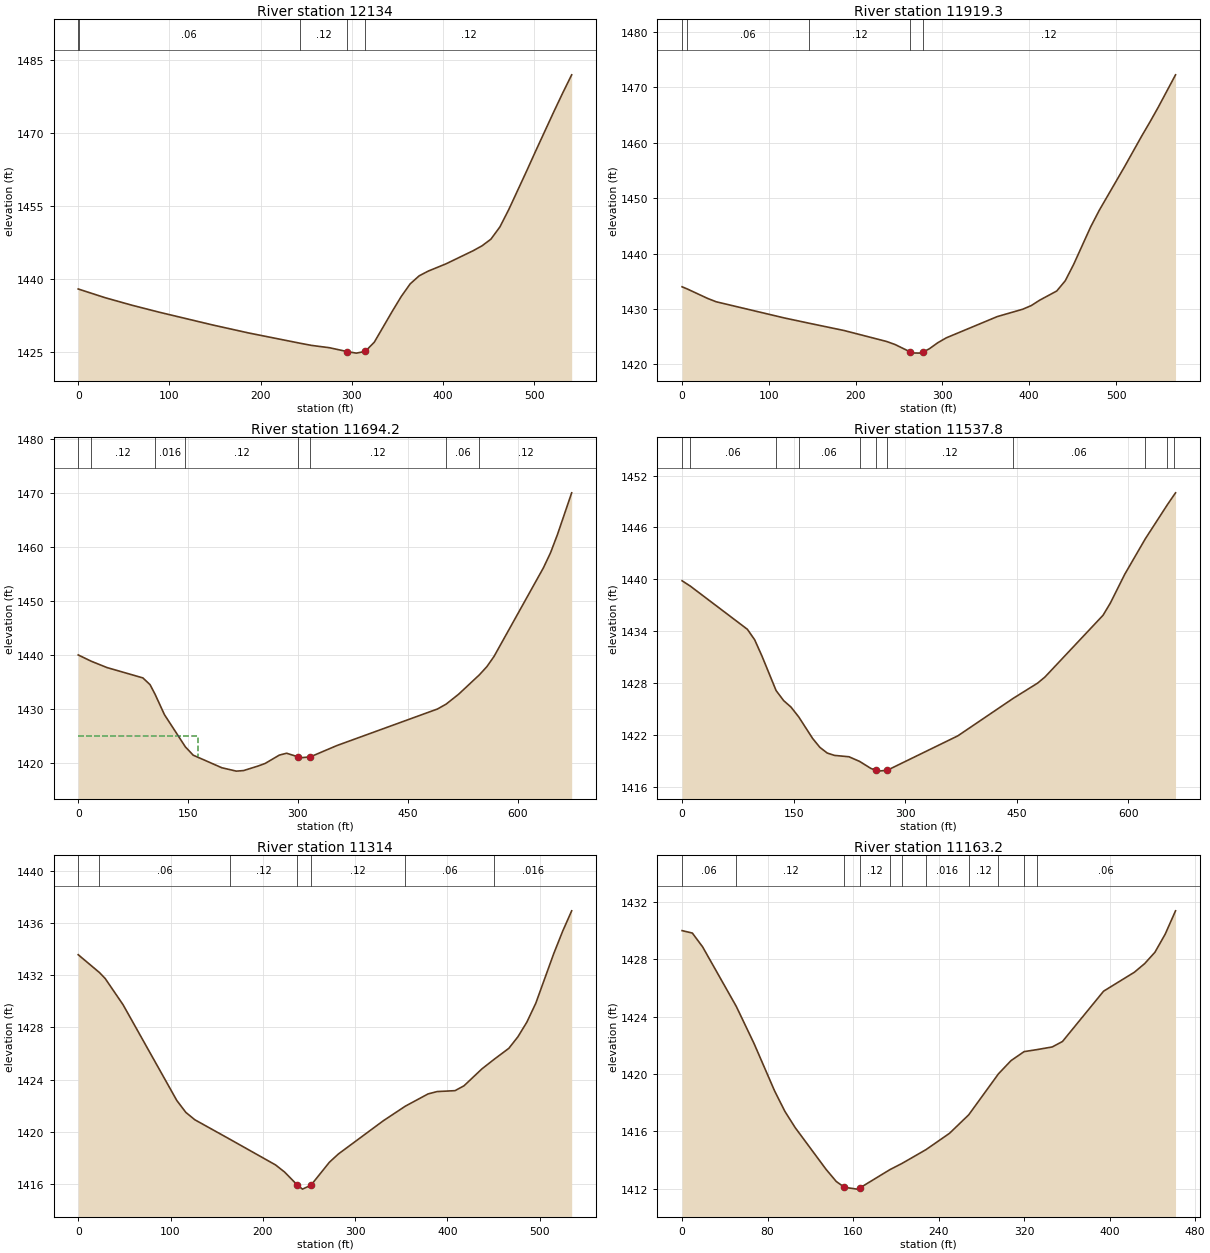
Type RM Length L Ch R = 1 ,12134   ,207,214.8,221.8
XS GIS Cut Line= 2
     1853125.937       278494.89      1853626.96       278699.74
#Sta/Elev= 30
       0    1438     .721437.954    29.5 1436.21      59 1434.66    88.6 1433.24
   147.6  1430.6     187 1428.96  242.92 1426.87   255.9 1426.41   275.6 1425.93
   295.2 1425.13   305.1 1424.82   314.9 1425.18   324.8 1427.07   344.4 1433.38
   354.3 1436.44   364.1 1439.04     374  1440.7   383.8 1441.66   403.5 1443.17
     433 1445.84   442.9 1446.86   452.7 1448.23   462.6 1450.76   472.4 1454.36
   492.1 1462.32   501.9 1466.38   521.6 1474.37   531.4 1478.24   541.3    1482
#Mann= 5 ,-1 , 0
       0    .016       0     .72     .06       0  242.92     .12       0
   295.2    .045       0   314.9     .12       0
Bank Sta=295.2,314.9
XS Rating Curve= 0 ,0
Exp/Cntr=0.3,0.1

Type RM Length L Ch R = 1 ,11919.3 ,248.9,225.1,200.5
XS GIS Cut Line= 3
     1853092.581      278611.102     1853337.189      278823.774
     1853574.532      278765.291
#Sta/Elev= 30
       0    1434    5.82 1433.62    29.5  1431.9    39.3  1431.3   117.9 1428.38
  146.11 1427.44   186.6 1426.12   235.7 1424.14   245.6 1423.58  262.84 1422.26
   265.2 1422.08     275 1422.04  277.58 1422.24   284.8 1422.81   294.7 1423.92
   304.5  1424.8   363.2 1428.63   392.6 1429.96   402.4 1430.62   412.1 1431.59
   431.7 1433.24   441.5 1435.08   451.2 1438.04   470.8  1444.8   480.6 1447.76
   509.9 1455.67   529.5 1461.15   539.2 1463.74     549 1466.47   568.6 1472.22
#Mann= 5 ,-1 , 0
       0    .016       0    5.82     .06       0  146.11     .12       0
  262.84    .045       0  277.58     .12       0
Bank Sta=262.84,277.58
XS Rating Curve= 0 ,0
Exp/Cntr=0.3,0.1

Type RM Length L Ch R = 1 ,11694.2 ,153.5,156.5,158.3
XS GIS Cut Line= 3
     1852926.809      279068.073     1853388.731      278902.805
     1853569.564      278873.277
#Sta/Elev= 30
       0    1440   17.931438.829    39.2 1437.67    88.3 1435.75    98.1  1434.5
  105.051432.699   117.7 1428.96  146.381422.981     157 1421.45   196.2 1419.12
   215.9  1418.5   225.7  1418.6   245.3 1419.43   255.1 1419.91   274.7 1421.47
   284.6 1421.81  300.221421.142   304.2 1420.98  316.791421.134   353.2 1423.23
   490.6    1430  502.651430.922   519.5 1432.74  547.821436.324   558.1 1437.85
   567.8 1439.73   635.2 1456.12   644.9  1458.9   654.5 1462.32   673.8    1470
#Mann= 8 ,-1 , 0
       0     .06       0   17.93     .12       0  105.05    .016       0
  146.38     .12       0  300.22    .045       0  316.79     .12       0
  502.65     .06       0  547.82     .12       0
#XS Ineff= 2 , 0
          163.91    1425
Permanent Ineff=
       F       F
Bank Sta=300.22,316.79
XS Rating Curve= 0 ,0
Exp/Cntr=0.3,0.1

Type RM Length L Ch R = 1 ,11537.8 ,233.1,223.7,213.8
XS GIS Cut Line= 2
     1852944.141      279182.932     1853587.012      279018.613
#Sta/Elev= 30
       0 1439.83   11.061439.215    87.8 1434.22    97.6 1433.01   107.3 1431.15
  126.431427.134   136.6 1425.97   146.4 1425.23  156.791424.098   175.6 1421.59
   185.4 1420.56   195.2 1419.91   204.9 1419.64   224.4 1419.48  238.761418.942
   253.7 1418.14  260.641417.917   263.5 1417.82  275.961417.922   370.8  1421.9
  445.191426.232   478.1    1428   487.9  1428.7     566 1435.84   575.7 1437.23
   595.2 1440.58  622.751444.669  652.441448.614  661.641449.768   663.5    1450
#Mann= 11 ,-1 , 0
       0     .12       0   11.06     .06       0  126.43    .016       0
  156.79     .06       0  238.76     .12       0  260.64    .045       0
  275.96     .12       0  445.19     .06       0  622.75     .12       0
  652.44     .06       0  661.64     .12       0
Bank Sta=260.64,275.96
XS Rating Curve= 0 ,0
Exp/Cntr=0.3,0.1

Type RM Length L Ch R = 1 ,11314   ,147.5,150.9,154.4
XS GIS Cut Line= 2
     1853133.039      279441.919     1853549.705       279106.85
#Sta/Elev= 30
       0 1433.57   23.041432.203    29.2 1431.75    48.6 1429.74   106.9  1422.4
   116.7 1421.49   126.4 1420.93   164.11419.449   213.9 1417.47   223.6 1416.93
   237.2 1415.95     243 1415.62   252.2 1415.92   272.2 1417.68   281.9 1418.31
   330.5 1420.85   354.51421.974   379.1 1422.91   388.9 1423.09   408.3 1423.16
     418 1423.53   437.5 1424.83  450.761425.564   466.6  1426.4   476.4 1427.28
   486.1  1428.4   495.8 1429.85   515.2 1433.64     525 1435.38   534.7 1436.93
#Mann= 7 ,-1 , 0
       0    .016       0   23.04     .06       0   164.1     .12       0
   237.2    .045       0   252.2     .12       0   354.5     .06       0
  450.76    .016       0
Bank Sta=237.2,252.2
XS Rating Curve= 0 ,0
Exp/Cntr=0.3,0.1

Type RM Length L Ch R = 1 ,11163.2 ,147.6,141.5,135.3
XS GIS Cut Line= 3
     1853256.573      279498.979     1853473.593      279374.517
     1853591.372      279198.864
#Sta/Elev= 30
       0    1430     9.6 1429.83    19.2 1428.87   50.711424.719    67.4 1422.12
    86.6 1418.82    96.2  1417.4   105.8 1416.27   134.7 1413.36   144.3 1412.51
  151.951412.108   163.6 1411.98  166.721412.081  194.471413.339  205.851413.775
   228.21414.732   250.2 1415.87  268.211417.161  296.031420.019   307.8 1420.94
  319.971421.564     3321421.705   346.3 1421.89   355.9 1422.27   394.4 1425.78
   423.2  1427.1   432.8  1427.7   442.4 1428.49     452 1429.75   461.7 1431.38
#Mann= 11 ,-1 , 0
       0     .06       0   50.71     .12       0  151.95    .045       0
  166.72     .12       0  194.47     .06       0  205.85     .12       0
   228.2    .016       0  268.21     .12       0  296.03    .016       0
  319.97     .08       0     332     .06       0
Bank Sta=151.95,166.72
XS Rating Curve= 0 ,0
Exp/Cntr=0.3,0.1

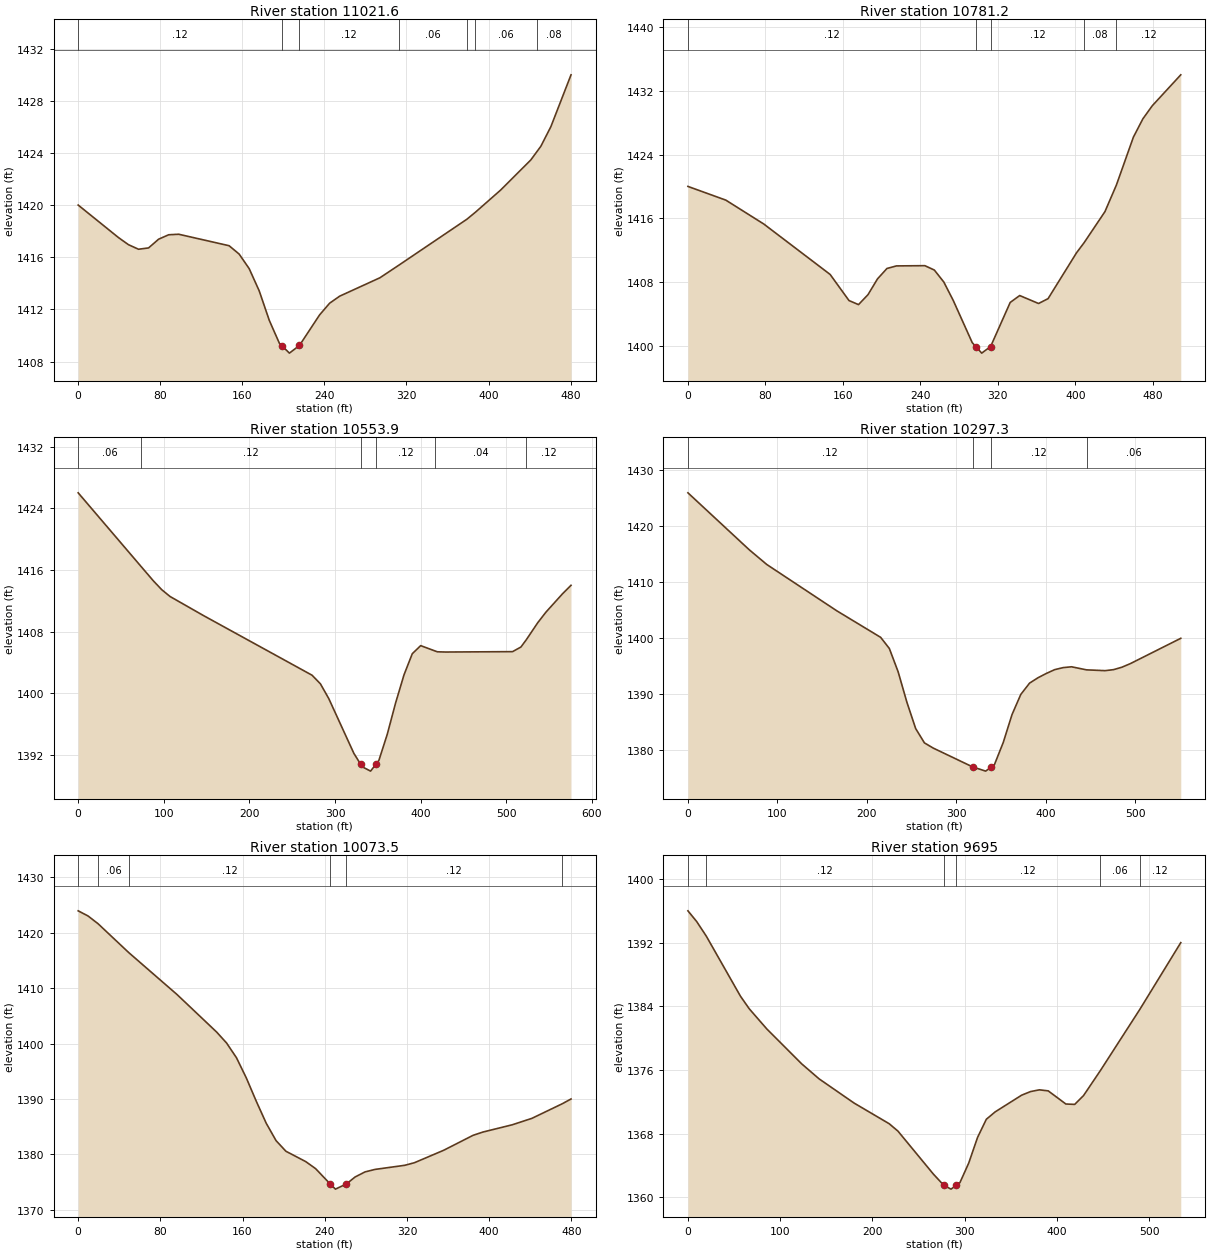
Type RM Length L Ch R = 1 ,11021.6 ,227.7,240.4,251.9
XS GIS Cut Line= 2
     1853347.566      279658.269     1853687.679      279318.986
#Sta/Elev= 30
       0 1420.01    39.2 1417.52      49 1416.97    58.8 1416.62    68.6 1416.72
    78.4 1417.39    88.2 1417.73      98 1417.77   147.1 1416.89   156.9 1416.25
   166.7 1415.13   176.5 1413.42   186.3 1411.16   196.1 1409.41  198.651409.211
   205.9 1408.65   215.7 1409.24   235.3 1411.58   245.1 1412.48   254.9 1413.02
   294.1 1414.43  312.291415.382  378.87 1418.92  387.161419.456   411.8 1421.16
   441.2 1423.47  447.041424.096     451 1424.52   460.8 1426.03   480.4    1430
#Mann= 7 ,-1 , 0
       0     .12       0  198.65    .045       0   215.7     .12       0
  312.29     .06       0  378.87     .08       0  387.16     .06       0
  447.04     .08       0
Bank Sta=198.65,215.7
XS Rating Curve= 0 ,0
Exp/Cntr=0.3,0.1

Type RM Length L Ch R = 1 ,10781.2 ,227,227.3,226.8
XS GIS Cut Line= 2
     1853383.437      279701.138     1853875.225       279570.67
#Sta/Elev= 30
       0    1420    39.1 1418.28    78.3 1415.28   146.8 1408.95   166.3 1405.67
   176.1 1405.16   185.9 1406.41   195.7 1408.39   205.5  1409.7   215.3 1410.02
   244.6 1410.05   254.4  1409.5   264.2 1407.99     274 1405.66   293.5 1400.39
   297.5 1399.85   303.3 1399.07   312.5  1399.9   332.7 1405.43   342.5  1406.3
     362  1405.3   371.8 1405.91   401.2 1411.67   409.11412.952   430.5 1416.83
  442.341420.172   459.9 1426.19   469.7 1428.49   479.4 1430.13   508.8 1434.01
#Mann= 5 ,-1 , 0
       0     .12       0   297.5    .045       0   312.5     .12       0
   409.1     .08       0  442.34     .12       0
Bank Sta=297.5,312.5
XS Rating Curve= 0 ,0
Exp/Cntr=0.3,0.1

Type RM Length L Ch R = 1 ,10553.9 ,249,256.6,263.8
XS GIS Cut Line= 2
     1853396.377      279931.955     1853952.127      279782.054
#Sta/Elev= 30
       0    1426   73.561416.437    87.8 1414.59    97.6 1413.44   107.3 1412.56
   146.3 1410.09   273.2 1402.35   282.9 1401.24   292.7 1399.32     322 1392.22
  329.861390.818   331.8 1390.48   341.5 1389.92  347.751390.816   351.2 1391.31
     361  1394.7   370.7 1398.75   380.5 1402.39   390.2 1405.14     400 1406.19
  417.261405.478   419.5 1405.39   429.3 1405.36   507.3 1405.41   517.1 1406.01
  523.521406.976   536.6 1409.14   546.3 1410.53   565.9 1412.94   575.6 1414.01
#Mann= 6 ,-1 , 0
       0     .06       0   73.56     .12       0  329.86    .045       0
  347.75     .12       0  417.26     .04       0  523.52     .12       0
Bank Sta=329.86,347.75
XS Rating Curve= 0 ,0
Exp/Cntr=0.3,0.1

Type RM Length L Ch R = 1 ,10297.3 ,222,223.8,225.3
XS GIS Cut Line= 3
     1853436.317      280071.486     1853817.243      280096.695
     1853968.619      280021.467
#Sta/Elev= 30
       0    1426    68.5 1415.83    88.1  1413.2   166.4 1404.92   215.4 1400.18
   225.1 1398.19   234.9 1394.04   244.7  1388.6   254.5 1383.89   264.3 1381.33
   274.1  1380.4  318.25 1377.03   332.8 1376.28  338.431376.957   342.6 1377.46
   352.4  1381.4   362.2 1386.38     372 1389.98   381.8    1392   391.2 1392.96
   400.5 1393.73   409.9 1394.41   419.3 1394.77   428.7 1394.92  445.461394.373
   466.3 1394.23   475.7 1394.41   485.1 1394.85   494.4 1395.48   550.8 1400.01
#Mann= 4 ,-1 , 0
       0     .12       0  318.25    .045       0  338.43     .12       0
  445.46     .06       0
Bank Sta=318.25,338.43
XS Rating Curve= 0 ,0
Exp/Cntr=0.3,0.1

Type RM Length L Ch R = 1 ,10073.5 ,389.2,378.6,365.6
XS GIS Cut Line= 3
     1853479.816      280277.623     1853794.454       280322.01
     1853935.184       280241.91
#Sta/Elev= 30
       0 1423.98     9.6 1423.05    19.3 1421.66    49.2 1416.44    96.3 1408.85
   134.8 1402.08   144.4 1400.12   154.1 1397.44   163.7 1393.78   173.3 1389.61
     183 1385.63   192.6 1382.48   202.2 1380.56   221.5 1378.69   231.1 1377.42
  245.431374.624   250.4 1373.72  261.091374.657   269.6 1375.92   279.2 1376.83
   288.9 1377.28   317.8 1378.02   327.3 1378.49   355.8 1380.74   384.4 1383.44
     394 1384.03   422.5 1385.34   441.6  1386.5  471.081389.129   479.7    1390
#Mann= 6 ,-1 , 0
       0    .016       0    19.3     .06       0    49.2     .12       0
  245.43    .045       0  261.09     .12       0  471.08     .06       0
Bank Sta=245.43,261.09
XS Rating Curve= 0 ,0
Exp/Cntr=0.3,0.1

Type RM Length L Ch R = 1 ,9695    ,154.3,152.4,150.4
XS GIS Cut Line= 3
     1853627.621      280576.033     1853828.544      280632.045
     1854138.163      280531.057
#Sta/Elev= 30
       0    1396     9.5 1394.65   19.891392.822    56.9 1385.28    66.4  1383.7
    85.3 1381.18   123.2 1376.78   142.2 1374.88   180.1 1371.84   218.2 1369.24
   227.7 1368.31   266.1 1362.91   277.3 1361.51   285.2 1361.02  291.031361.505
   294.8 1361.82   304.4 1364.29     314 1367.52   323.5  1369.8   333.1 1370.73
   361.8 1372.83   371.4 1373.28     381  1373.5   390.6 1373.37   409.7 1371.72
   419.3 1371.67   428.9 1372.78  447.041375.902  489.931383.614   534.3    1392
#Mann= 6 ,-1 , 0
       0    .016       0   19.89     .12       0   277.3    .045       0
  291.03     .12       0  447.04     .06       0  489.93     .12       0
Bank Sta=277.3,291.03
XS Rating Curve= 0 ,0
Exp/Cntr=0.3,0.1

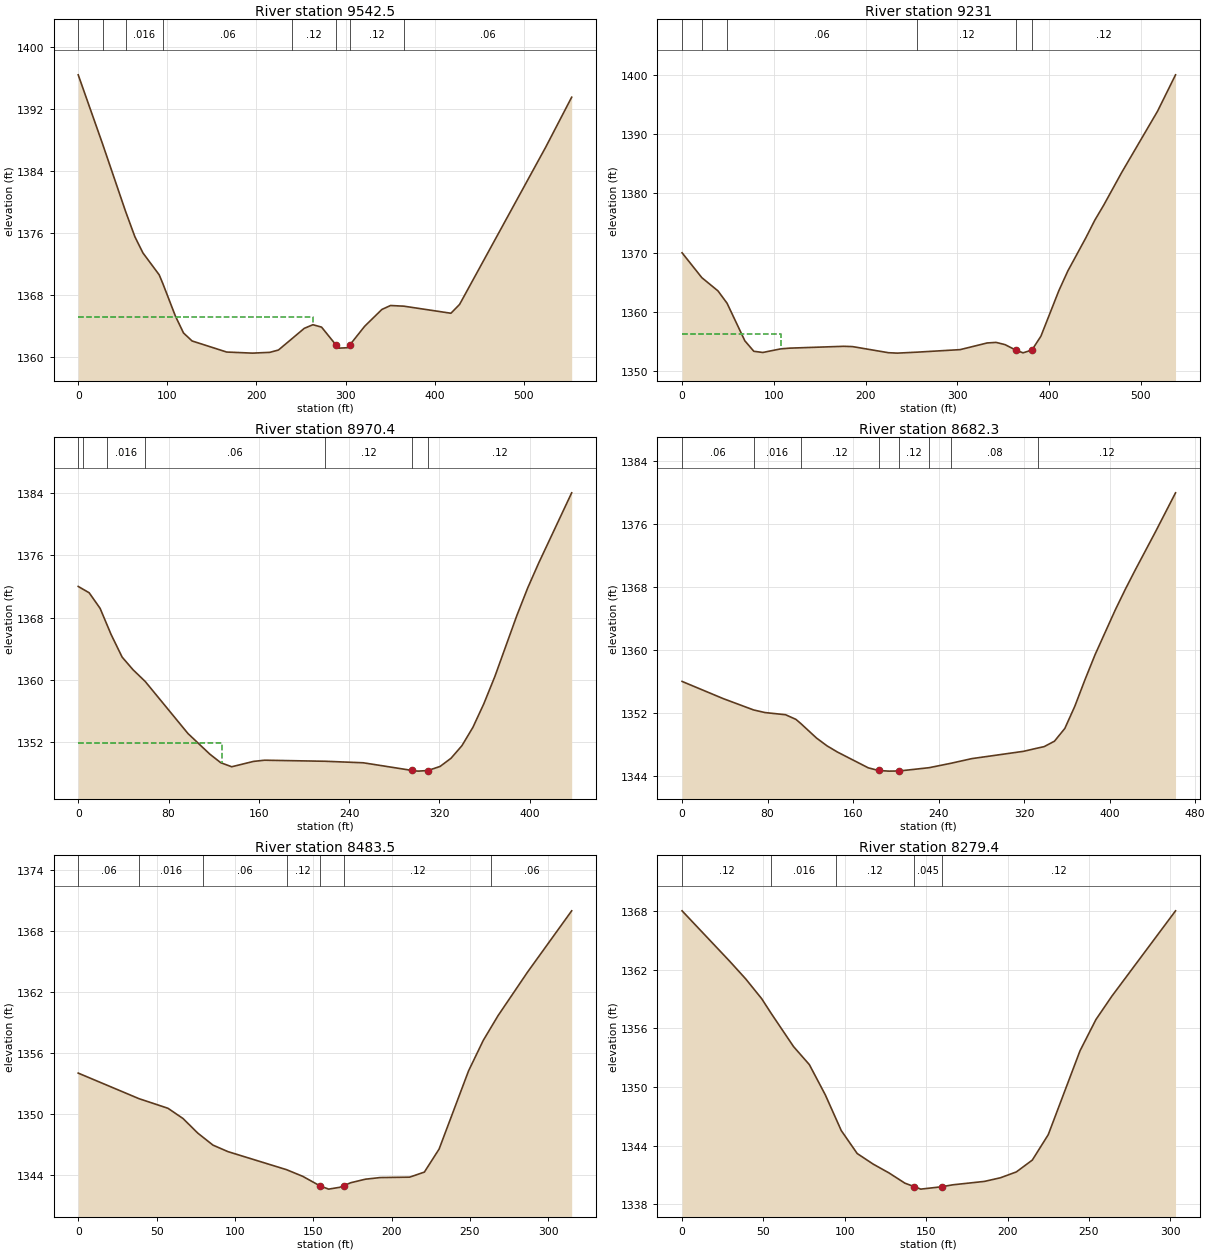
Type RM Length L Ch R = 1 ,9542.5  ,310.2,311.5,311.7
XS GIS Cut Line= 3
      1853659.08      280829.072     1853777.136      280823.864
     1854178.178      280653.725
#Sta/Elev= 30
       0 1396.41   27.311387.497   53.191378.763    63.6  1375.5    72.7  1373.4
    90.9 1370.58   95.051369.431   109.1 1365.25   118.2 1363.07   127.8 1362.04
   166.6 1360.61   195.6 1360.47     215 1360.57   224.7 1360.87  240.461362.388
   253.7 1363.67   263.4 1364.14   273.1 1363.83  289.611361.479   292.4 1361.11
   302.1 1361.17  304.541361.489   321.5 1363.94   340.8 1366.11   350.5 1366.62
  365.431366.534   418.3 1365.62     428 1366.76   524.8  1387.1   553.8 1393.52
#Mann= 8 ,-1 , 0
       0     .12       0   27.31     .06       0   53.19    .016       0
   95.05     .06       0  240.46     .12       0  289.61    .045       0
  304.54     .12       0  365.43     .06       0
#XS Ineff= 2 , 0
          263.78  1365.2
Permanent Ineff=
       F       F
Bank Sta=289.61,304.54
XS Rating Curve= 0 ,0
Exp/Cntr=0.3,0.1

Type RM Length L Ch R = 1 ,9231    ,250.8,260.7,270.3
XS GIS Cut Line= 2
     1853817.319      281097.687     1854316.591      280897.862
#Sta/Elev= 30
       0    1370   21.521365.811    39.1 1363.58   49.011361.504    68.4 1355.17
    78.2  1353.4      88  1353.2   107.6 1353.81   117.3 1353.93     176 1354.24
   185.8 1354.19   224.9 1353.16   234.7 1353.09   256.21353.254   303.1 1353.68
   332.4  1354.8   342.2  1354.9     352 1354.52  363.931353.584   371.6 1353.14
   381.3 1353.61   391.1 1355.95   410.7 1363.64   420.4 1366.93     440 1372.51
   449.8 1375.49   459.6 1378.05   479.1 1383.53   518.2 1393.86   537.8 1399.99
#Mann= 6 ,-1 , 0
       0     .08       0   21.52    .016       0   49.01     .06       0
   256.2     .12       0  363.93    .045       0   381.3     .12       0
#XS Ineff= 2 , 0
          107.94 1356.25
Permanent Ineff=
       F       F
Bank Sta=363.93,381.3
XS Rating Curve= 0 ,0
Exp/Cntr=0.3,0.1

Type RM Length L Ch R = 1 ,8970.4  ,302.3,288.1,273.7
XS GIS Cut Line= 2
     1853843.588      281199.647     1854280.195      281221.584
#Sta/Elev= 30
       0 1371.99    3.961371.659     9.7 1371.18    19.4 1369.18   25.131367.207
    29.1 1365.84    38.9 1362.93    48.6  1361.3   59.341359.806    97.2 1353.13
   116.6 1350.48   126.3 1349.38     136 1348.86   155.4 1349.55   165.2  1349.7
  218.961349.564   252.6 1349.37  296.061348.382   301.2  1348.3   309.9 1348.38
   320.6  1348.9   330.3 1349.95     340 1351.57   349.7 1353.92   359.4 1356.95
   369.2 1360.46   388.6 1368.25   398.3 1371.82     408    1375   437.2    1384
#Mann= 7 ,-1 , 0
       0     .06       0    3.96     .08       0   25.13    .016       0
   59.34     .06       0  218.96     .12       0  296.06    .045       0
   309.9     .12       0
#XS Ineff= 2 , 0
          127.64 1351.97
Permanent Ineff=
       F       F
Bank Sta=296.06,309.9
XS Rating Curve= 0 ,0
Exp/Cntr=0.3,0.1

Type RM Length L Ch R = 1 ,8682.3  ,197.9,198.8,199.6
XS GIS Cut Line= 3
     1853892.432       281564.19     1854195.403      281373.277
     1854295.851      281347.779
#Sta/Elev= 30
       0 1355.99    38.7 1353.79   66.941352.359    77.4 1352.03    96.8 1351.75
   106.5 1351.16  110.981350.642   125.8 1348.78   135.5  1347.8   145.2 1347.01
   174.2 1344.99   183.9 1344.65   193.6 1344.57   203.2 1344.59  231.141345.007
  251.491345.567     271 1346.16   319.4 1347.09  332.79 1347.51   338.8 1347.69
   348.4 1348.38   358.1    1350   367.5 1352.84     377 1356.22   386.4 1359.39
   405.2 1365.06   414.6 1367.69     424 1370.18   442.9 1375.03   461.7    1380
#Mann= 8 ,-1 , 0
       0     .06       0   66.94    .016       0  110.98     .12       0
   183.9    .045       0   203.2     .12       0  231.14     .06       0
  251.49     .08       0  332.79     .12       0
Bank Sta=183.9,203.2
XS Rating Curve= 0 ,0
Exp/Cntr=0.3,0.1

Type RM Length L Ch R = 1 ,8483.5  ,202.1,204,202.9
XS GIS Cut Line= 4
     1854008.549      281688.616     1854151.715      281635.099
     1854165.621       281619.32     1854302.852      281586.841
#Sta/Elev= 26
       0    1354   38.791351.479    57.3 1350.53    66.9 1349.52    76.4 1348.07
   79.821347.653      86  1346.9    95.5 1346.26  132.921344.479   143.3 1343.82
   154.3 1342.88   159.8 1342.56   166.9 1342.74   169.3 1342.89   173.9 1343.19
   183.3 1343.54   192.7  1343.7   211.5 1343.74   220.9 1344.24   230.3 1346.51
   249.1 1354.22   258.5 1357.23  263.591358.546   267.9 1359.66   286.7 1363.95
   314.9    1370
#Mann= 7 ,-1 , 0
       0     .06       0   38.79    .016       0   79.82     .06       0
  132.92     .12       0   154.3    .045       0   169.3     .12       0
  263.59     .06       0
Bank Sta=154.3,169.3
XS Rating Curve= 0 ,0
Exp/Cntr=0.3,0.1

Type RM Length L Ch R = 1 ,8279.4  ,246.8,245.8,242.3
XS GIS Cut Line= 2
     1854070.446      281845.718     1854343.396      281713.619
#Sta/Elev= 27
       0    1368    29.4 1362.82    39.1 1361.04    48.9 1359.02   54.841357.493
    68.5 1354.12    78.2 1352.28      88 1349.19   94.47 1346.78    97.8 1345.54
   107.6 1343.19   117.4 1342.11   127.2  1341.2   136.9 1340.16  142.721339.799
   146.7 1339.55  159.481339.792   166.3 1339.99   185.8 1340.34   195.6 1340.71
   205.4 1341.31   215.2 1342.52     225 1345.12   244.5 1353.69   254.3 1356.89
   264.1 1359.28   303.2    1368
#Mann= 5 ,-1 , 0
       0     .12       0   54.84    .016       0   94.47     .12       0
  142.72    .045       0  159.48     .12       0
Bank Sta=142.72,159.48
XS Rating Curve= 0 ,0
Exp/Cntr=0.3,0.1

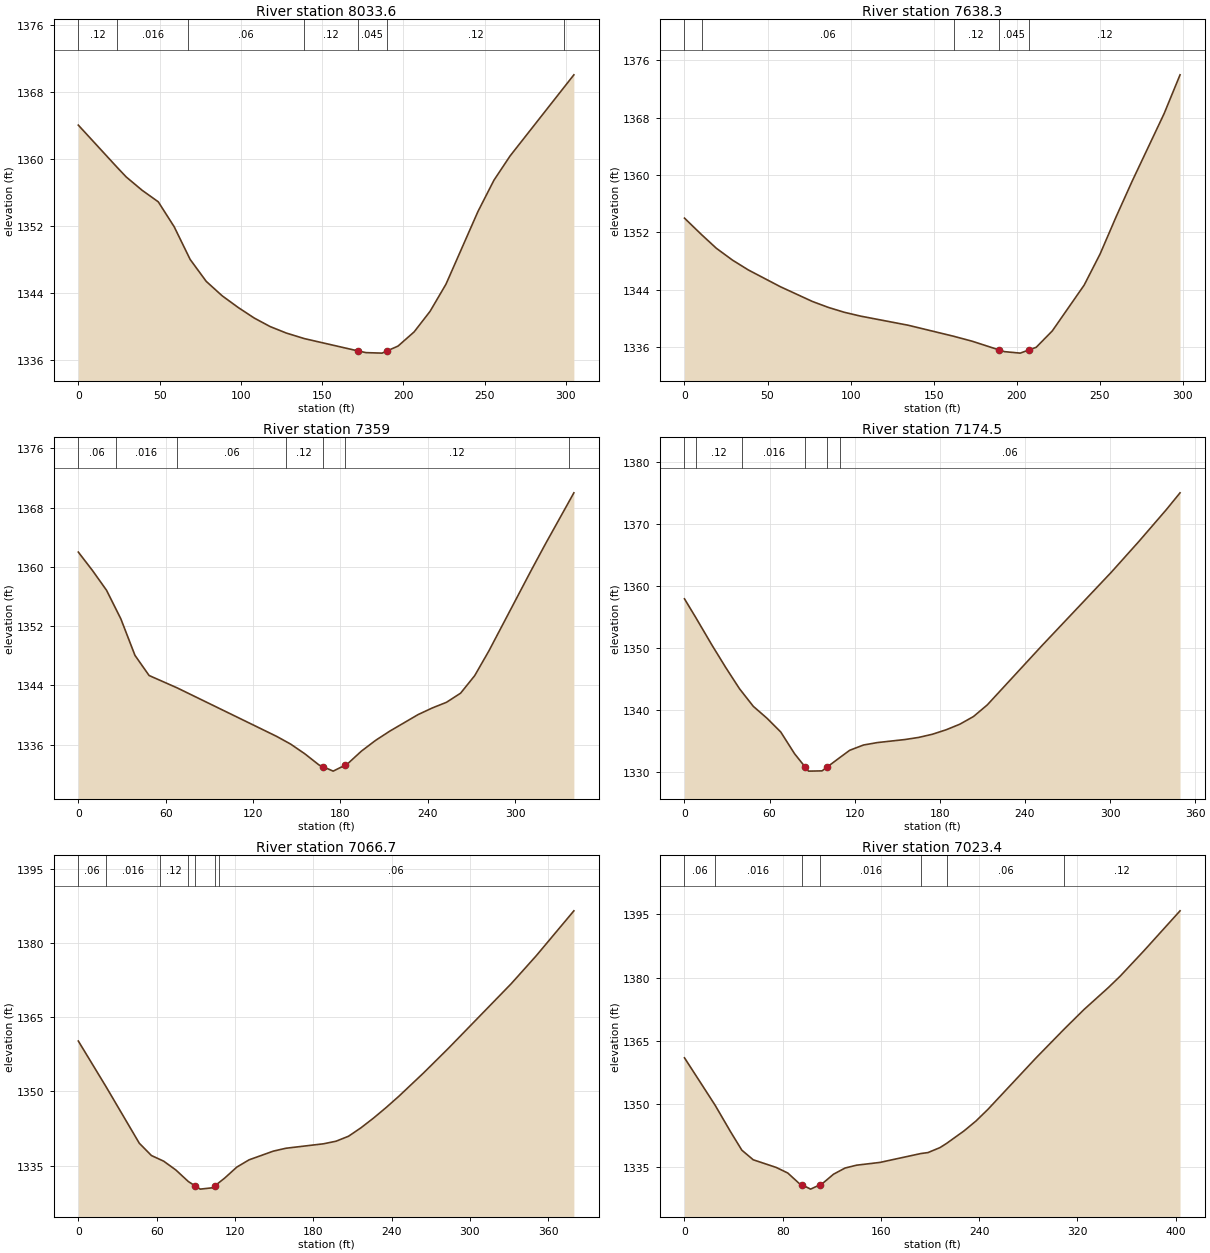
Type RM Length L Ch R = 1 ,8033.6  ,393.7,395.3,395.7
XS GIS Cut Line= 2
     1854201.454      282060.741     1854453.412      281889.037
#Sta/Elev= 28
       0    1364   23.931358.952    29.5 1357.81    39.3 1356.22    49.2 1354.85
      59 1351.87   67.361348.552    68.8 1347.98    78.7 1345.36    88.5 1343.64
    98.4 1342.24   108.2 1340.99     118 1339.97   127.9  1339.2  139.041338.534
  171.92 1337.07     177 1336.86   186.9  1336.8  189.78 1337.05   196.7 1337.64
   206.6 1339.33   216.4 1341.78   226.2 1345.02   245.9  1353.7   255.7 1357.42
   265.6 1360.31  298.811368.502   304.9    1370
#Mann= 7 ,-1 , 0
       0     .12       0   23.93    .016       0   67.36     .06       0
  139.04     .12       0  171.92    .045       0  189.78     .12       0
  298.81     .06       0
Bank Sta=171.92,189.78
XS Rating Curve= 0 ,0
Exp/Cntr=0.3,0.1

Type RM Length L Ch R = 1 ,7638.3  ,274.2,279.3,284
XS GIS Cut Line= 2
      1854417.99      282319.565     1854673.895      282166.206
#Sta/Elev= 25
       0    1354   10.381351.673    19.2 1349.79    28.9 1348.14    38.5 1346.76
    57.7 1344.43      77 1342.37    86.6 1341.54    96.2 1340.86   105.9 1340.33
   134.7 1339.05  161.961337.517   173.2 1336.82  189.281335.612   192.5 1335.37
   202.1 1335.16  207.521335.621   211.7 1335.97   221.4 1338.26   240.6 1344.66
   250.2 1349.01   259.8 1354.18   269.5 1359.17   288.7 1368.58   298.3    1374
#Mann= 5 ,-1 , 0
       0    .016       0   10.38     .06       0  161.96     .12       0
  189.28    .045       0  207.52     .12       0
Bank Sta=189.28,207.52
XS Rating Curve= 0 ,0
Exp/Cntr=0.3,0.1

Type RM Length L Ch R = 1 ,7359    ,186.6,184.5,181.1
XS GIS Cut Line= 2
     1854498.464      282534.695     1854821.183      282426.777
#Sta/Elev= 30
       0    1362     9.7 1359.52    19.4 1356.84   25.571354.416    29.2 1352.99
    38.9 1348.06    48.6 1345.34   67.98 1343.66   136.1 1337.13  142.66 1336.42
   145.8 1336.08   155.6 1334.76   165.3 1333.26   167.8 1333.05     175 1332.43
   182.8 1333.19   184.7 1333.38   194.4 1335.13   204.2 1336.59   213.9 1337.83
   233.3 1340.06   243.1 1340.96   252.8 1341.72   262.5 1342.95   272.2 1345.32
     282 1348.68   311.1 1359.57   320.8 1363.11  336.71 1368.73   340.3    1370
#Mann= 7 ,-1 , 0
       0     .06       0   25.57    .016       0   67.98     .06       0
  142.66     .12       0   167.8    .045       0   182.8     .12       0
  336.71     .06       0
Bank Sta=167.8,182.8
XS Rating Curve= 0 ,0
Exp/Cntr=0.3,0.1

Type RM Length L Ch R = 1 ,7174.5  ,117.4,107.8,97.9
XS GIS Cut Line= 2
     1854594.844      282683.094     1854908.646      282529.448
#Sta/Elev= 30
       0    1358    8.161354.904    19.4 1350.53    29.1 1346.92    38.8  1343.5
   40.791342.919    48.5 1340.67    58.2 1338.74    67.9 1336.52    77.6 1333.03
   85.011330.905    87.4 1330.22      97 1330.26  100.631330.889  109.721332.441
   116.5 1333.58   126.2 1334.43   135.9 1334.82   155.3 1335.31     165 1335.65
   174.7 1336.16   184.4 1336.88   194.1 1337.78   203.8 1339.03   213.5  1340.9
   252.3 1350.52   300.9 1362.28   320.3 1367.23   339.7 1372.37   349.4 1375.09
#Mann= 6 ,-1 , 0
       0     .06       0    8.16     .12       0   40.79    .016       0
   85.01    .045       0  100.63     .12       0  109.72     .06       0
Bank Sta=85.01,100.63
XS Rating Curve= 0 ,0
Exp/Cntr=0.3,0.1

Type RM Length L Ch R = 1 ,7066.7  ,43.4,43.3,43.4
XS GIS Cut Line= 3
     1854688.245      282796.466     1854781.621      282679.794
     1854958.125      282532.052
#Sta/Elev= 30
       0 1360.19   21.33 1350.92    46.7 1339.54      56 1337.05   62.331336.282
    65.4 1335.91    74.7 1334.13   84.34 1331.78   89.481330.918    93.4 1330.26
   102.7 1330.53  104.391330.881  107.491331.527   112.1 1332.49   121.4 1334.71
   130.8 1336.18   149.4 1337.94     159 1338.52   187.8 1339.42   197.4 1339.94
     207 1340.95   216.6 1342.67   226.2 1344.63   235.8 1346.75   245.3 1348.97
   264.5 1353.75   283.7 1358.77   331.7  1371.8   350.8 1377.43   379.6  1386.5
#Mann= 7 ,-1 , 0
       0     .06       0   21.33    .016       0   62.33     .12       0
   84.34    .016       0   89.48    .045       0  104.39    .016       0
  107.49     .06       0
Bank Sta=89.48,104.39
XS Rating Curve= 0 ,0
Exp/Cntr=0.3,0.1

Type RM Length L Ch R = 1 ,7023.4  ,125,124.5,123
XS GIS Cut Line= 3
     1854720.225      282825.758     1854813.602      282709.086
     1855008.907      282546.375
#Sta/Elev= 30
       0 1360.97   24.921349.754    37.4 1343.52    46.7 1339.09      56 1336.81
    74.7    1335    84.1 1333.68    93.4 1331.21   95.491330.911   102.7 1329.86
  110.481330.907   112.1 1331.12   121.4  1333.4   130.8 1334.86   140.1 1335.53
   159.2 1336.19  192.551338.295   198.3 1338.52   208.1  1339.7  213.391340.677
   227.6 1343.64   237.4    1346   247.2 1348.78   286.3 1360.95  309.421367.831
   325.4 1372.42     345 1377.56   354.8 1380.31   374.3 1386.37   403.6  1395.8
#Mann= 7 ,-1 , 0
       0     .06       0   24.92    .016       0   95.49    .045       0
  110.48    .016       0  192.55     .08       0  213.39     .06       0
  309.42     .12       0
Bank Sta=95.49,110.48
XS Rating Curve= 0 ,0
Exp/Cntr=0.3,0.1