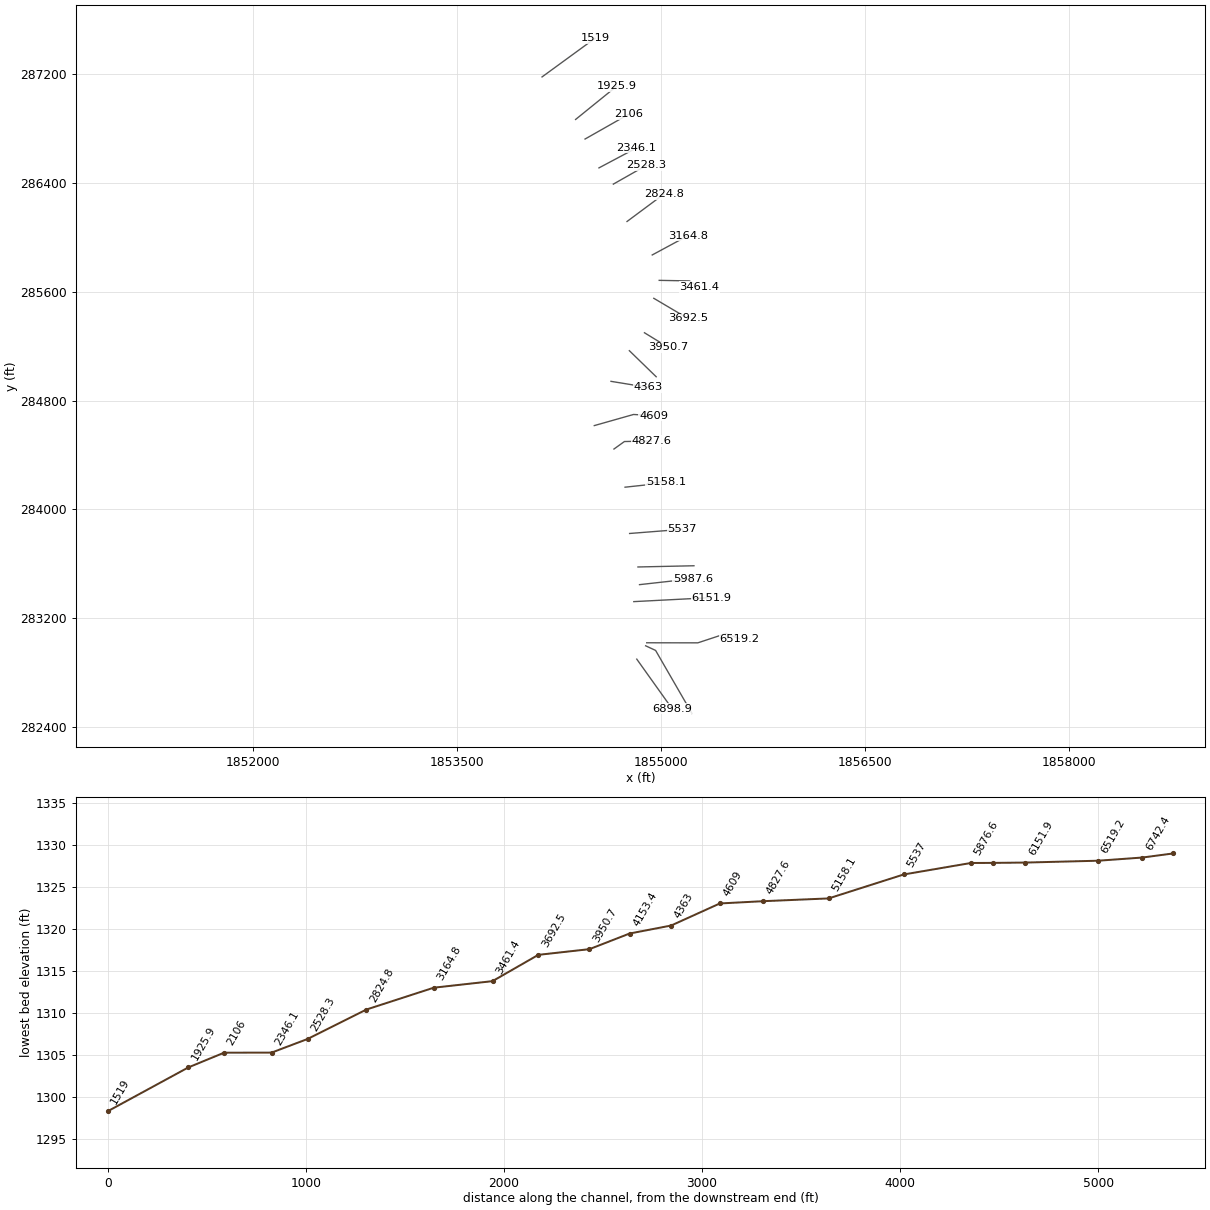
HEC-RAS study LCOVERN.prj: LCOVERN

--- LCOVERN.g01 (geometry) --- (continued)

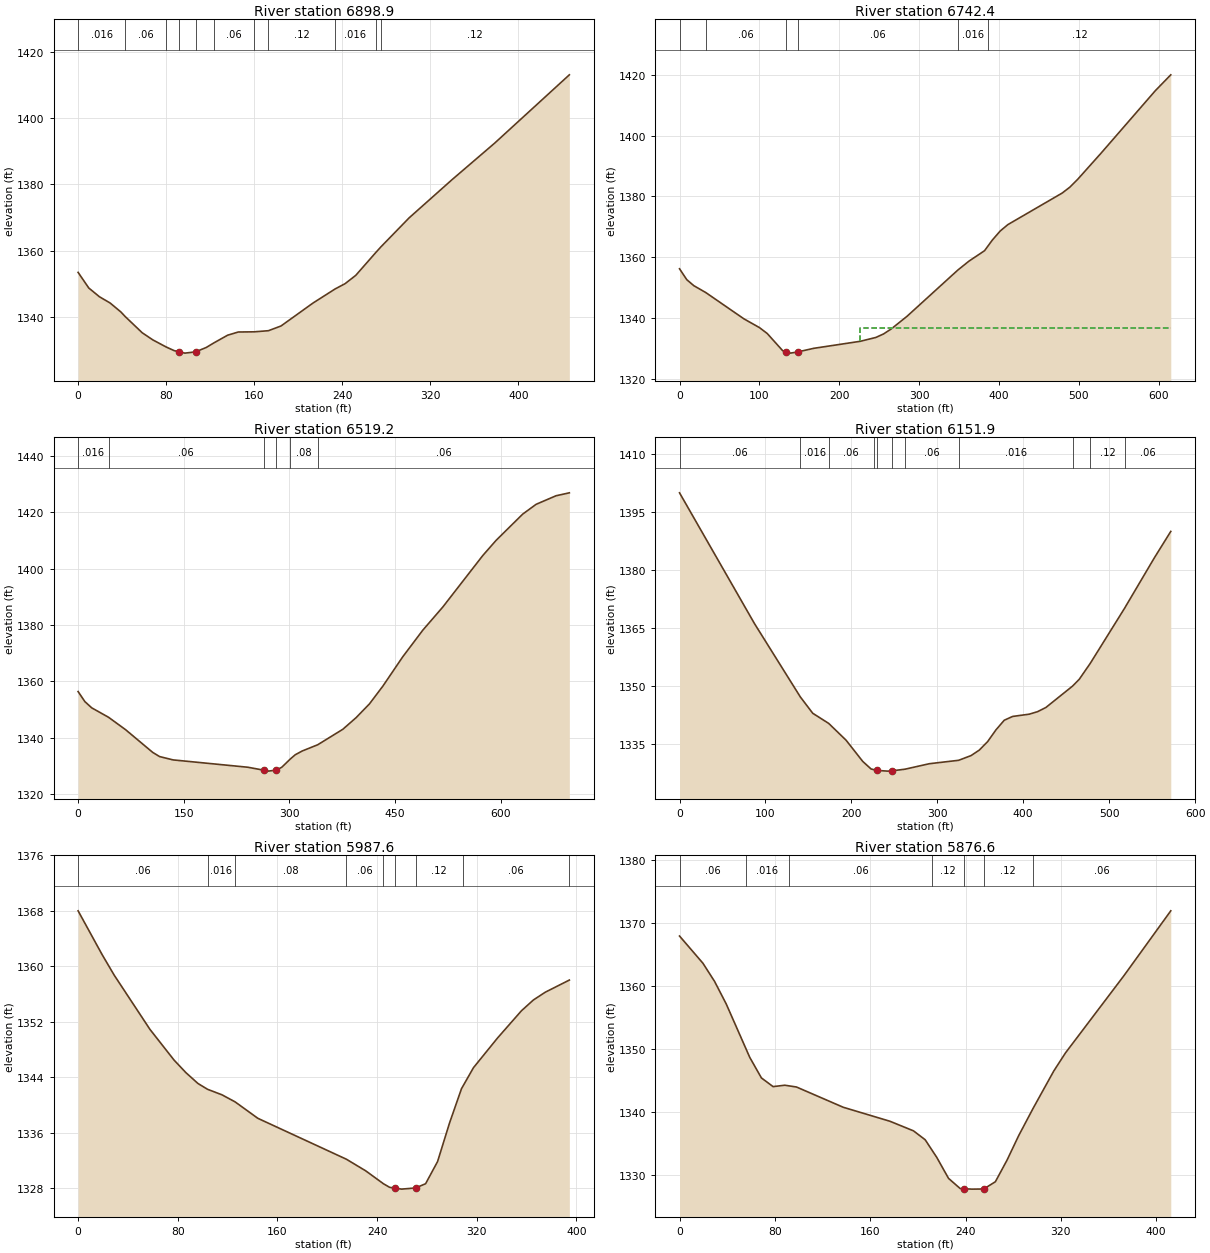
Type RM Length L Ch R = 1 ,6898.9  ,156.5,156.5,154.8
XS GIS Cut Line= 2
     1854824.011       282899.24     1855083.125      282535.959
#Sta/Elev= 30
       0  1353.4     9.7 1348.67    19.4 1346.02    29.1 1344.13    38.8 1341.44
   42.781340.037    58.2 1335.14    67.9 1332.97   80.211330.787    87.3 1329.72
   92.011329.354      97 1328.97   106.7 1329.35   116.4 1330.68  123.331332.066
   135.8 1334.39   145.5 1335.36  160.051335.415  172.861335.753   184.3 1337.18
   213.4 1344.13  233.48 1348.39   242.5 1349.98   252.2  1352.5   270.21359.332
  274.88 1361.06   300.7  1369.9   339.5  1381.4   378.3 1392.48   446.2 1413.16
#Mann= 11 ,-1 , 0
       0    .016       0   42.78     .06       0   80.21     .12       0
   92.01    .045       0   106.7     .12       0  123.33     .06       0
  160.05     .08       0  172.86     .12       0  233.48    .016       0
   270.2     .06       0  274.88     .12       0
Bank Sta=92.01,106.7
XS Rating Curve= 0 ,0
Exp/Cntr=0.3,0.1

Type RM Length L Ch R = 1 ,6742.4  ,197.7,223.2,246.4
XS GIS Cut Line= 3
      1854889.37       282997.24     1854962.507      282963.276
       1855229.9      282500.343
#Sta/Elev= 30
       0 1356.22       9 1352.66    17.9 1350.66   32.831348.407    80.6 1339.76
   100.1 1336.87   109.8 1334.94   129.2 1329.27  133.521328.918     139 1328.48
   148.7 1328.91   168.1 1330.06   226.4 1332.37   245.9 1333.64   255.6  1334.8
   265.3 1336.47   284.8 1340.57  348.561355.805   362.5 1358.74     382 1362.17
  386.721363.863   391.7 1365.65   401.4 1368.59   411.1 1370.73   479.2 1381.12
   488.9 1383.08   498.6 1385.63   527.8 1394.21   595.8 1414.77   615.2    1420
#Mann= 6 ,-1 , 0
       0    .016       0   32.83     .06       0  133.52    .045       0
   148.7     .06       0  348.56    .016       0  386.72     .12       0
#XS Ineff= 2 , 0
                          225.87          1336.6
Permanent Ineff=
       F       F
Bank Sta=133.52,148.7
XS Rating Curve= 0 ,0
Exp/Cntr=0.3,0.1

Type RM Length L Ch R = 1 ,6519.2  ,366.4,367.3,368.2
XS GIS Cut Line= 4
     1854897.136      283019.481      1855273.06      283019.002
     1855479.821      283087.153     1855577.277      283050.867
#Sta/Elev= 30
       0 1356.35     9.6 1352.79    19.3 1350.57   43.291347.209    67.5  1342.8
     106 1334.74   115.7 1333.27     135 1332.08     241 1329.48  263.36 1328.45
   269.9  1328.1  281.491328.455   289.2 1329.47  301.461332.431   308.4 1333.92
   318.1 1335.23  340.291337.465   375.9 1342.95   394.8 1347.09   413.8 1351.99
   432.7 1358.25   461.1 1368.72   489.5 1378.14   517.9 1386.36   574.7 1404.65
   593.6 1410.03   631.4 1419.35   650.4 1422.82   678.7 1425.86   697.6  1426.9
#Mann= 6 ,-1 , 0
       0    .016       0   43.29     .06       0  263.36    .045       0
  281.49     .12       0  301.46     .08       0  340.29     .06       0
Bank Sta=263.36,281.49
XS Rating Curve= 0 ,0
Exp/Cntr=0.3,0.1

Type RM Length L Ch R = 1 ,6151.9  ,163.1,164.3,165.6
XS GIS Cut Line= 2
     1854802.168      283322.096     1855373.139      283351.624
#Sta/Elev= 30
       0    1400    87.2 1366.12  140.591347.106     155 1342.88  173.591340.247
   193.8  1335.9   213.2  1330.4   222.9 1328.44  226.211328.252  229.441328.069
   242.3 1327.88  246.951327.942   262.41328.381   290.7  1329.8  324.831330.685
   339.2  1331.9   348.8 1333.32   358.6 1335.54   368.2 1338.56   377.9 1341.07
   387.6 1342.05     407 1342.64   416.7 1343.29   426.4 1344.38  457.331349.906
   465.1 1351.66  478.041355.826  517.85 1370.06   552.4 1383.09   571.7    1390
#Mann= 11 ,-1 , 0
       0     .06       0  140.59    .016       0  173.59     .06       0
  226.21     .12       0  229.44    .045       0  246.95     .12       0
   262.4     .06       0  324.83    .016       0  457.33     .06       0
  478.04     .12       0  517.85     .06       0
Bank Sta=229.44,246.95
XS Rating Curve= 0 ,0
Exp/Cntr=0.3,0.1

Type RM Length L Ch R = 1 ,5987.6  ,112.9,111,108.8
XS GIS Cut Line= 2
     1854844.356      283446.912     1855236.288      283490.788
#Sta/Elev= 30
       0    1368    19.2 1361.71    28.9 1358.74    57.7 1350.89      77 1346.47
    86.6 1344.64    96.2 1343.09  103.941342.243   115.4 1341.46  126.051340.431
   144.3 1338.06  215.381332.156   230.9 1330.48  245.161328.615   250.1  1328.1
  254.411327.983   259.7 1327.84  270.981328.012     279 1328.62   288.6 1331.82
   298.2 1337.38   307.8 1342.33  308.72 1342.62   317.4 1345.36   336.7 1349.64
   355.9 1353.57   365.5 1355.13   375.1 1356.26  394.061357.979   394.4 1358.01
#Mann= 9 ,-1 , 0
       0     .06       0  103.94    .016       0  126.05     .08       0
  215.38     .06       0  245.16     .12       0  254.41    .045       0
  270.98     .12       0  308.72     .06       0  394.06    .016       0
Bank Sta=254.41,270.98
XS Rating Curve= 0 ,0
Exp/Cntr=0.3,0.1

Type RM Length L Ch R = 1 ,5876.6  ,338.5,339.6,340.7
XS GIS Cut Line= 2
     1854832.699      283576.932     1855244.762      283585.834
#Sta/Elev= 30
       0    1368    19.6 1363.69    29.4  1360.8    39.2 1357.21   55.521350.205
    58.9 1348.75    68.7 1345.48    78.5  1344.1    88.3 1344.32   91.771344.221
    98.1 1344.04   137.4 1340.82   176.6  1338.6   196.3 1337.08   206.1 1335.67
  211.641334.076   215.9 1332.85   225.7 1329.54   235.5 1327.92  238.571327.894
   245.3 1327.83   255.2 1327.85     265    1329   274.8 1332.43   284.6 1336.33
  296.611340.627     314 1346.57   323.8 1349.44   372.9 1361.71   412.2    1372
#Mann= 7 ,-1 , 0
       0     .06       0   55.52    .016       0   91.77     .06       0
  211.64     .12       0  238.57    .045       0   255.2     .12       0
  296.61     .06       0
Bank Sta=238.57,255.2
XS Rating Curve= 0 ,0
Exp/Cntr=0.3,0.1

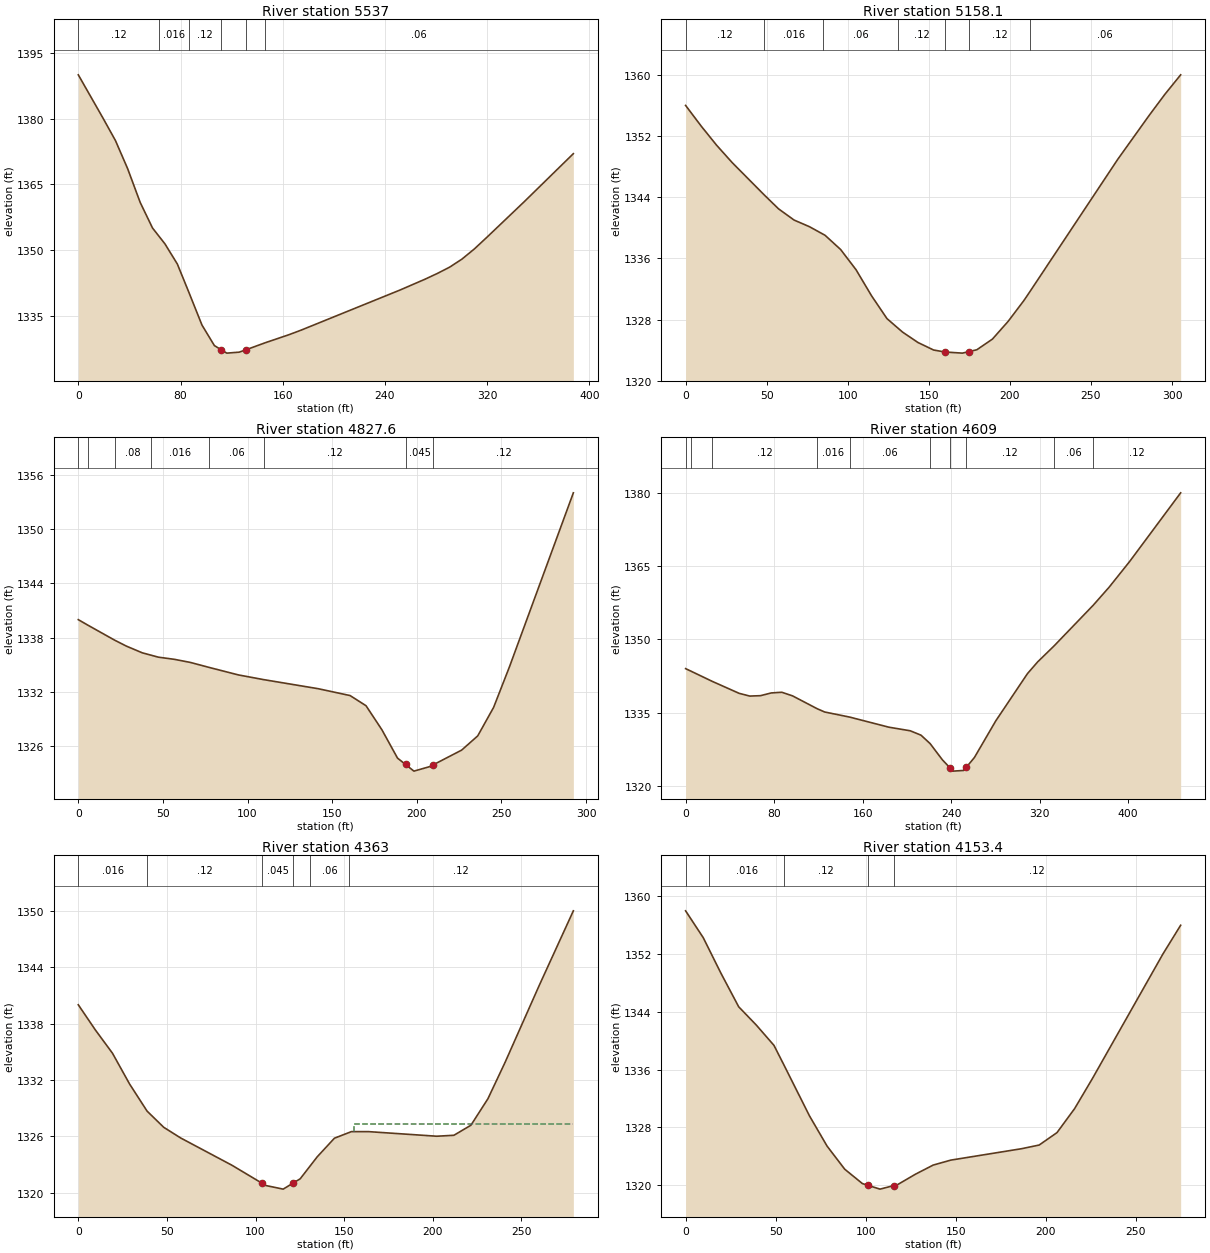
Type RM Length L Ch R = 1 ,5537    ,371.4,378.9,383.5
XS GIS Cut Line= 2
     1854771.455      283823.199     1855157.663      283853.593
#Sta/Elev= 28
       0    1390    19.4 1380.08    29.1 1374.98    38.7 1368.52    48.4 1360.89
    58.1 1355.02   63.42 1353.04    67.8 1351.41    77.5 1346.81    86.41340.442
    96.8 1332.86   106.5 1328.18  111.931327.216   116.2 1326.46   125.9 1326.68
     131  1327.2  146.081328.807   164.6 1330.64   174.3  1331.7   251.8 1340.87
   271.2 1343.32   280.9 1344.64   290.6 1346.09   300.2 1347.92   309.9 1350.24
   319.6 1352.87   348.7 1360.96   387.4    1372
#Mann= 6 ,-1 , 0
       0     .12       0   63.42    .016       0    86.4     .12       0
  111.93    .045       0     131     .12       0  146.08     .06       0
Bank Sta=111.93,131
XS Rating Curve= 0 ,0
Exp/Cntr=0.3,0.1

Type RM Length L Ch R = 1 ,5158.1  ,338.8,330.5,323.9
XS GIS Cut Line= 4
      1854737.93      284163.574     1854889.929      284180.013
      1854912.86      284193.668     1855038.069      284205.297
#Sta/Elev= 30
       0    1356     9.6  1353.3    19.1  1350.8    28.7 1348.53   48.551344.285
    57.3 1342.48    66.9 1341.01    76.4 1340.14   84.561339.188      86 1339.02
    95.6 1337.16   105.1 1334.52   114.7  1331.1   124.2 1328.12  131.18 1326.84
   133.8 1326.36   143.3    1325   152.9 1324.02   159.8 1323.76   170.7 1323.61
   174.8 1323.81   179.6 1324.05   189.2 1325.44   198.9 1327.76   208.6 1330.48
   212.3 1331.64   266.6 1348.98     286 1354.73   295.6 1357.46   305.3    1360
#Mann= 7 ,-1 , 0
       0     .12       0   48.55    .016       0   84.56     .06       0
  131.18     .12       0   159.8    .045       0   174.8     .12       0
   212.3     .06       0
Bank Sta=159.8,174.8
XS Rating Curve= 0 ,0
Exp/Cntr=0.3,0.1

Type RM Length L Ch R = 1 ,4827.6  ,212.6,218.6,224.3
XS GIS Cut Line= 3
     1854656.242      284444.144     1854733.072      284499.339
     1854930.936      284503.199
#Sta/Elev= 26
       0    1340    5.96 1339.36   21.521337.732    28.4 1337.08    37.8 1336.34
   42.771336.089    47.3 1335.86    56.8 1335.62    66.2 1335.28   77.421334.722
    94.6  1333.9  109.691333.375   141.7 1332.38   160.6 1331.62     170  1330.5
   179.4 1327.84   188.6 1324.72  193.371324.012   198.3 1323.28   207.7 1323.78
  209.861323.991   226.5  1325.6     236 1327.17   245.4 1330.32   254.8 1334.82
   292.5    1354
#Mann= 8 ,-1 , 0
       0     .12       0    5.96     .06       0   21.52     .08       0
   42.77    .016       0   77.42     .06       0  109.69     .12       0
  193.37    .045       0  209.86     .12       0
Bank Sta=193.37,209.86
XS Rating Curve= 0 ,0
Exp/Cntr=0.3,0.1

Type RM Length L Ch R = 1 ,4609    ,255.9,246,236.1
XS GIS Cut Line= 3
     1854511.638      284616.532     1854800.066      284698.267
     1854947.593      284690.207
#Sta/Elev= 30
       0    1344    4.751343.491   23.961341.406    48.4 1338.94      58 1338.38
    67.7 1338.46    77.4 1339.02      87 1339.16    96.7 1338.42  118.921335.791
   125.7 1335.12  148.291334.077   183.7 1332.01   203.1 1331.27   212.8 1330.37
  221.061328.641   232.1 1325.33   238.71323.751   241.8 1323.01   251.4 1323.15
  253.731323.786   261.1 1325.81   280.4 1333.31     309 1342.97   318.2 1345.37
  333.111348.658   368.5 1356.99   382.9 1360.69   401.4 1365.94   447.5    1380
#Mann= 10 ,-1 , 0
       0     .12       0    4.75     .08       0   23.96     .12       0
  118.92    .016       0  148.29     .06       0  221.06     .12       0
   238.7    .045       0  253.73     .12       0  333.11     .06       0
   368.5     .12       0
Bank Sta=238.7,253.73
XS Rating Curve= 0 ,0
Exp/Cntr=0.3,0.1

Type RM Length L Ch R = 1 ,4363    ,223,209.5,195.3
XS GIS Cut Line= 2
     1854634.525      284941.908     1854910.159      284896.856
#Sta/Elev= 26
       0    1340     9.6 1337.33    19.3 1334.84    28.9 1331.58   38.811328.683
    48.2 1326.96    57.8 1325.82    86.7 1322.92  103.791320.993   105.9 1320.76
   115.6 1320.38  121.211321.026   125.2 1321.48  130.531322.779   134.8 1323.82
   144.5  1325.8  152.811326.406   154.1  1326.5   163.7  1326.5   202.2 1326.01
   211.9 1326.11   221.5 1327.18   231.1    1330   240.8 1333.88     260 1342.04
   279.3    1350
#Mann= 6 ,-1 , 0
       0    .016       0   38.81     .12       0  103.79    .045       0
  121.21     .12       0  130.53     .06       0  152.81     .12       0
#XS Ineff= 2 , 0
                          155.73          1327.3
Permanent Ineff=
       F       F
Bank Sta=103.79,121.21
XS Rating Curve= 0 ,0
Exp/Cntr=0.3,0.1

Type RM Length L Ch R = 1 ,4153.4  ,197.6,202.7,207.7
XS GIS Cut Line= 2
     1854769.538       285167.28     1854966.805       284975.64
#Sta/Elev= 26
       0    1358     9.8 1354.28   13.111352.622    19.6 1349.37    29.5  1344.7
    39.3 1342.16    49.1 1339.35    54.71336.601    68.8 1329.59    78.6 1325.39
    88.4 1322.19    98.2  1320.2  101.52 1319.94     108 1319.43   115.71319.925
   117.8 1320.06   127.7  1321.5   137.5 1322.76   147.3 1323.45   186.6 1325.03
   196.4 1325.54   206.3 1327.26   216.1 1330.59   225.9 1334.72   265.2 1352.04
     275    1356
#Mann= 5 ,-1 , 0
       0     .12       0   13.11    .016       0    54.7     .12       0
  101.52    .045       0   115.7     .12       0
Bank Sta=101.52,115.7
XS Rating Curve= 0 ,0
Exp/Cntr=0.3,0.1

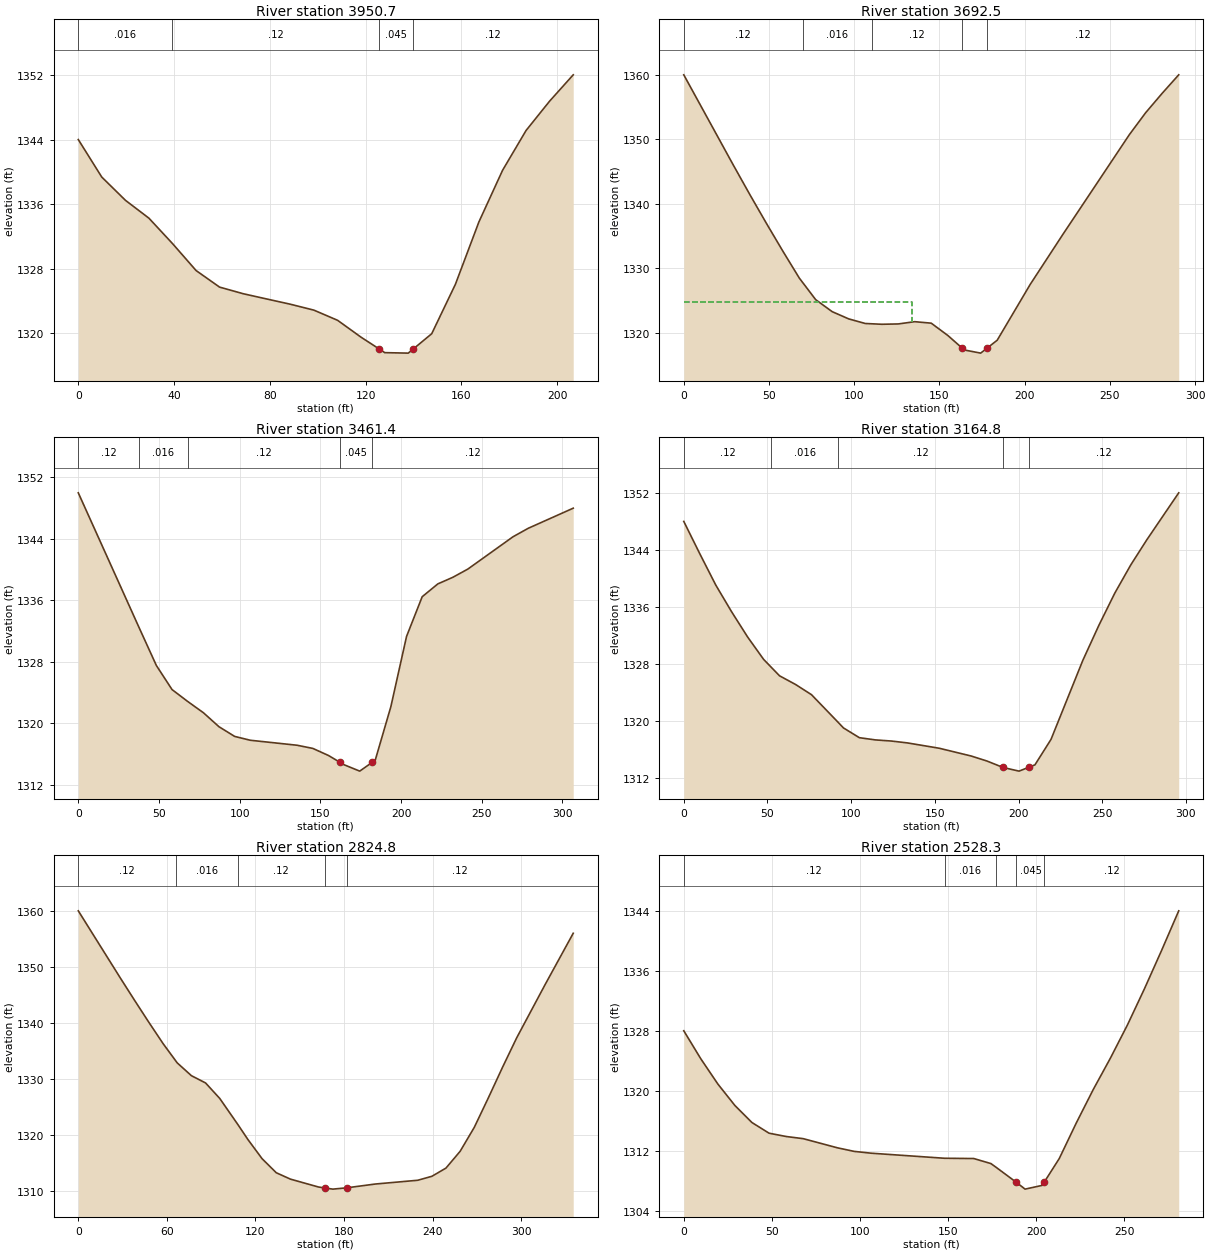
Type RM Length L Ch R = 1 ,3950.7  ,257.9,258.2,258.5
XS GIS Cut Line= 2
     1854880.588      285299.167     1855056.927      285191.348
#Sta/Elev= 26
       0    1344     9.8 1339.36    19.7 1336.48    29.5 1334.27   39.211331.171
    39.4 1331.11    49.2 1327.79      59 1325.74    68.9 1324.92    78.7 1324.27
    88.6 1323.62    98.4 1322.89   108.3 1321.63   118.1 1319.54   124.8 1318.25
  125.531318.109     128 1317.63   137.8 1317.57   139.8 1318.06   147.6 1319.97
   157.5 1326.09   167.3  1333.8   177.2  1340.2     187 1345.12   196.8 1348.74
   206.7 1352.01
#Mann= 4 ,-1 , 0
       0    .016       0   39.21     .12       0  125.53    .045       0
   139.8     .12       0
Bank Sta=125.53,139.8
XS Rating Curve= 0 ,0
Exp/Cntr=0.3,0.1

Type RM Length L Ch R = 1 ,3692.5  ,219.5,231.2,242.8
XS GIS Cut Line= 2
     1854949.486      285552.439     1855199.529      285404.731
#Sta/Elev= 28
       0    1360      29 1346.05    38.7 1341.48    48.4 1337.03    58.1  1332.7
    67.8 1328.51   69.891327.783    77.4 1325.17    87.1 1323.31    96.8 1322.19
   106.5 1321.48  110.231321.434   116.2 1321.36   125.8 1321.41   135.5 1321.76
   145.2 1321.53   154.9 1319.63  163.091317.728   164.6 1317.38   174.2 1316.89
  178.141317.702   183.9 1318.89   203.3 1327.55   222.6 1335.35   261.4 1350.72
     271 1354.13   280.7 1357.14   290.4    1360
#Mann= 5 ,-1 , 0
       0     .12       0   69.89    .016       0  110.23     .12       0
  163.09    .045       0  178.14     .12       0
#XS Ineff= 2 , 0
          133.64 1324.75
Permanent Ineff=
       F       F
Bank Sta=163.09,178.14
XS Rating Curve= 0 ,0
Exp/Cntr=0.3,0.1

Type RM Length L Ch R = 1 ,3461.4  ,284.9,296.5,308
XS GIS Cut Line= 3
     1854989.074      285684.519     1855211.825      285680.389
     1855283.136      285636.084
#Sta/Elev= 26
       0    1350   37.611332.481    48.4 1327.51    58.1 1324.38   67.771322.835
    77.5 1321.37    87.2 1319.54    96.9 1318.28   106.6 1317.78   135.6 1317.13
   145.3 1316.72     155  1315.8  162.161314.907   164.7 1314.59   174.4 1313.76
  182.091314.898     184 1315.18   193.7 1322.16   203.4 1331.29   213.1 1336.47
   222.8 1338.14   232.1    1339   241.4 1340.07   269.4 1344.28   278.8 1345.38
   306.7    1348
#Mann= 5 ,-1 , 0
       0     .12       0   37.61    .016       0   67.77     .12       0
  162.16    .045       0  182.09     .12       0
Bank Sta=162.16,182.09
XS Rating Curve= 0 ,0
Exp/Cntr=0.3,0.1

Type RM Length L Ch R = 1 ,3164.8  ,336.5,340,343.1
XS GIS Cut Line= 2
     1854937.778      285871.309     1855198.043      286011.598
#Sta/Elev= 30
       0    1348     9.5  1343.5    19.1 1339.08    28.6 1335.32    38.2 1331.77
    47.7 1328.65   52.351327.524    57.2 1326.35    66.8 1325.13    76.3  1323.7
   92.371319.788    95.4 1319.04   104.9 1317.67   114.4 1317.36     124  1317.2
   133.5 1316.94   152.6 1316.19   171.7  1315.1   181.2 1314.39   190.8 1313.49
   200.3 1312.98  206.171313.524   209.8 1313.86   219.4 1317.43   238.4 1328.51
     248 1333.43   257.5 1337.94     267 1341.88   276.6 1345.41   295.7 1352.01
#Mann= 5 ,-1 , 0
       0     .12       0   52.35    .016       0   92.37     .12       0
   190.8    .045       0  206.17     .12       0
Bank Sta=190.8,206.17
XS Rating Curve= 0 ,0
Exp/Cntr=0.3,0.1

Type RM Length L Ch R = 1 ,2824.8  ,301.2,296.5,293.6
XS GIS Cut Line= 2
     1854752.409      286117.372     1855021.497      286317.336
#Sta/Elev= 30
       0    1360    28.7 1347.93    38.3 1343.97    47.9 1340.08    57.5  1336.3
   66.111333.209      67 1332.89    76.6 1330.61    86.2 1329.31    95.8 1326.55
   108.21321.851   114.9 1319.22   124.5  1315.8   134.1  1313.3   143.7 1312.16
   162.8 1310.75  166.751310.599   172.4 1310.38     182 1310.62   201.2 1311.29
   229.9 1311.96   239.5 1312.67     249 1314.13   258.6 1317.12   268.2  1321.4
   277.8  1326.7   287.4 1332.15   296.9 1337.35   316.1 1346.82   335.2    1356
#Mann= 5 ,-1 , 0
       0     .12       0   66.11    .016       0   108.2     .12       0
  166.75    .045       0     182     .12       0
Bank Sta=166.75,182
XS Rating Curve= 0 ,0
Exp/Cntr=0.3,0.1

Type RM Length L Ch R = 1 ,2528.3  ,180.4,182.2,181.7
XS GIS Cut Line= 2
     1854651.721      286392.193     1854896.016      286530.758
#Sta/Elev= 27
       0    1328     9.7 1324.25    19.4 1320.88      29 1318.04    38.7 1315.76
    48.4 1314.34    58.1  1313.9    67.8 1313.61    87.2 1312.39    96.8 1311.91
   106.5 1311.67  147.981310.997   164.6 1310.96   174.3 1310.29  177.271309.788
  188.821307.774   193.7 1306.88   203.4 1307.38  204.721307.866   213.1 1310.96
   222.8 1315.72   232.4 1320.17   242.1 1324.34   251.8 1328.78   261.5 1333.63
   271.2 1338.73   280.9    1344
#Mann= 5 ,-1 , 0
       0     .12       0  147.98    .016       0  177.27     .12       0
  188.82    .045       0  204.72     .12       0
Bank Sta=188.82,204.72
XS Rating Curve= 0 ,0
Exp/Cntr=0.3,0.1

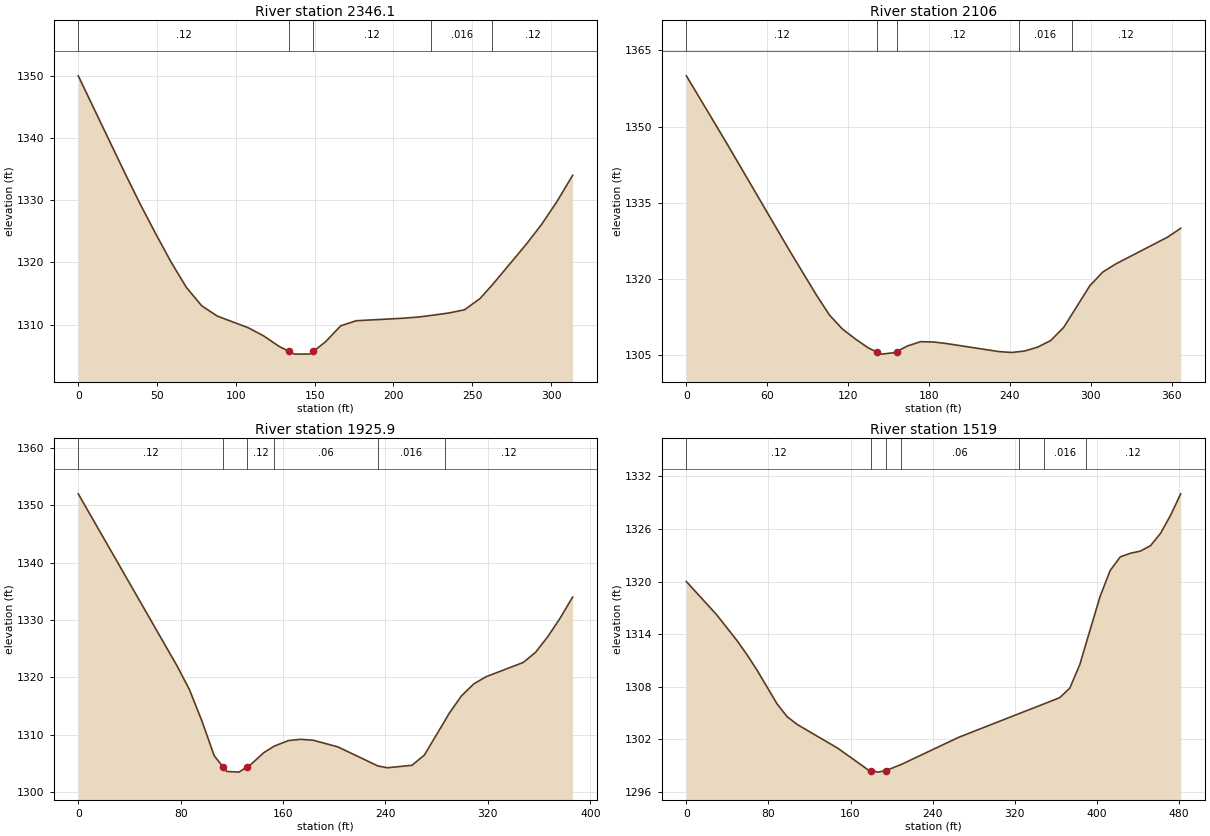
Type RM Length L Ch R = 1 ,2346.1  ,239.3,240,240.5
XS GIS Cut Line= 2
     1854545.943      286511.524     1854822.952      286658.711
#Sta/Elev= 29
       0    1350    29.4 1334.46    39.2 1329.43      49 1324.68    58.8  1320.1
    68.6 1315.98    78.4 1313.01    88.2 1311.37   107.8  1309.5   117.6 1308.19
   127.4  1306.5  133.781305.684   137.2 1305.25     147 1305.27  149.221305.707
   156.8 1307.21   166.6 1309.81   176.4 1310.62   205.9 1311.02   215.7 1311.21
  223.851311.468   235.3 1311.87   245.1 1312.38   254.9 1314.17  262.871316.423
   284.3 1322.92   294.1 1326.13   303.9 1329.83   313.7    1334
#Mann= 5 ,-1 , 0
       0     .12       0  133.78    .045       0  149.22     .12       0
  223.85    .016       0  262.87     .12       0
Bank Sta=133.78,149.22
XS Rating Curve= 0 ,0
Exp/Cntr=0.3,0.1

Type RM Length L Ch R = 1 ,2106    ,176.4,180.1,183.8
XS GIS Cut Line= 2
      1854443.66       286723.75     1854762.606      286904.774
#Sta/Elev= 29
       0    1360      29 1347.16    77.2 1325.32    96.5 1316.86   106.2 1312.92
   115.8 1310.17   125.5  1308.2   135.1 1306.44   141.21305.682   144.8 1305.24
   154.4 1305.53  155.931305.737   164.1 1306.85   173.7 1307.69   183.4 1307.63
     193 1307.32   231.6 1305.75   241.3 1305.56   246.81305.726   250.9 1305.85
   260.6 1306.62   270.2  1307.9   279.9  1310.5   285.91313.025   299.2 1318.66
   308.8 1321.37   318.5 1322.98   357.1 1328.28   366.7    1330
#Mann= 5 ,-1 , 0
       0     .12       0   141.2    .045       0  155.93     .12       0
   246.8    .016       0   285.9     .12       0
Bank Sta=141.2,155.93
XS Rating Curve= 0 ,0
Exp/Cntr=0.3,0.1

Type RM Length L Ch R = 1 ,1925.9  ,408.1,407,405.8
XS GIS Cut Line= 2
     1854374.041      286867.632     1854674.304       287110.58
#Sta/Elev= 30
       0    1352    77.2    1322    86.9 1317.86    96.6 1312.41   106.2 1306.36
  113.171304.385   115.9 1303.61   125.5 1303.49  131.711304.385   135.2 1304.89
   144.8 1306.86     153 1308.01   164.2 1308.99   173.8 1309.21   183.5 1309.05
   202.8 1307.89   234.11304.566   241.4 1304.25   260.7 1304.68   270.4 1306.46
  286.51 1312.48   289.7 1313.71   299.3 1316.76     309 1318.87   318.6 1320.12
   347.6  1322.6   357.3 1324.38   366.9 1327.13   376.6 1330.38   386.2    1334
#Mann= 6 ,-1 , 0
       0     .12       0  113.17    .045       0  131.71     .12       0
     153     .06       0   234.1    .016       0  286.51     .12       0
Bank Sta=113.17,131.71
XS Rating Curve= 0 ,0
Exp/Cntr=0.3,0.1

Type RM Length L Ch R = 1 ,1519    ,240,233,226.7
XS GIS Cut Line= 2
     1854127.184      287180.364     1854516.415      287464.206
#Sta/Elev= 30
       0    1320    29.5 1316.22    49.2 1313.29      59 1311.68    68.8 1309.91
    88.5 1306.03    98.3 1304.58   108.1  1303.7   147.5    1301     177 1298.54
  180.22 1298.45   186.8 1298.27  194.531298.452  209.261299.135   265.4 1302.24
  324.091304.936  348.141306.033   363.8 1306.76   373.6 1307.84   383.4 1310.53
  389.311312.876   403.1 1318.28   412.9 1321.24   422.8 1322.81   432.6 1323.22
   442.4 1323.47   452.2 1324.08   462.1  1325.5   471.9 1327.57   481.7    1330
#Mann= 7 ,-1 , 0
       0     .12       0  180.22    .045       0  194.53     .12       0
  209.26     .06       0  324.09     .12       0  348.14    .016       0
  389.31     .12       0
Bank Sta=180.22,194.53
XS Rating Curve= 0 ,0
Exp/Cntr=0.3,0.1