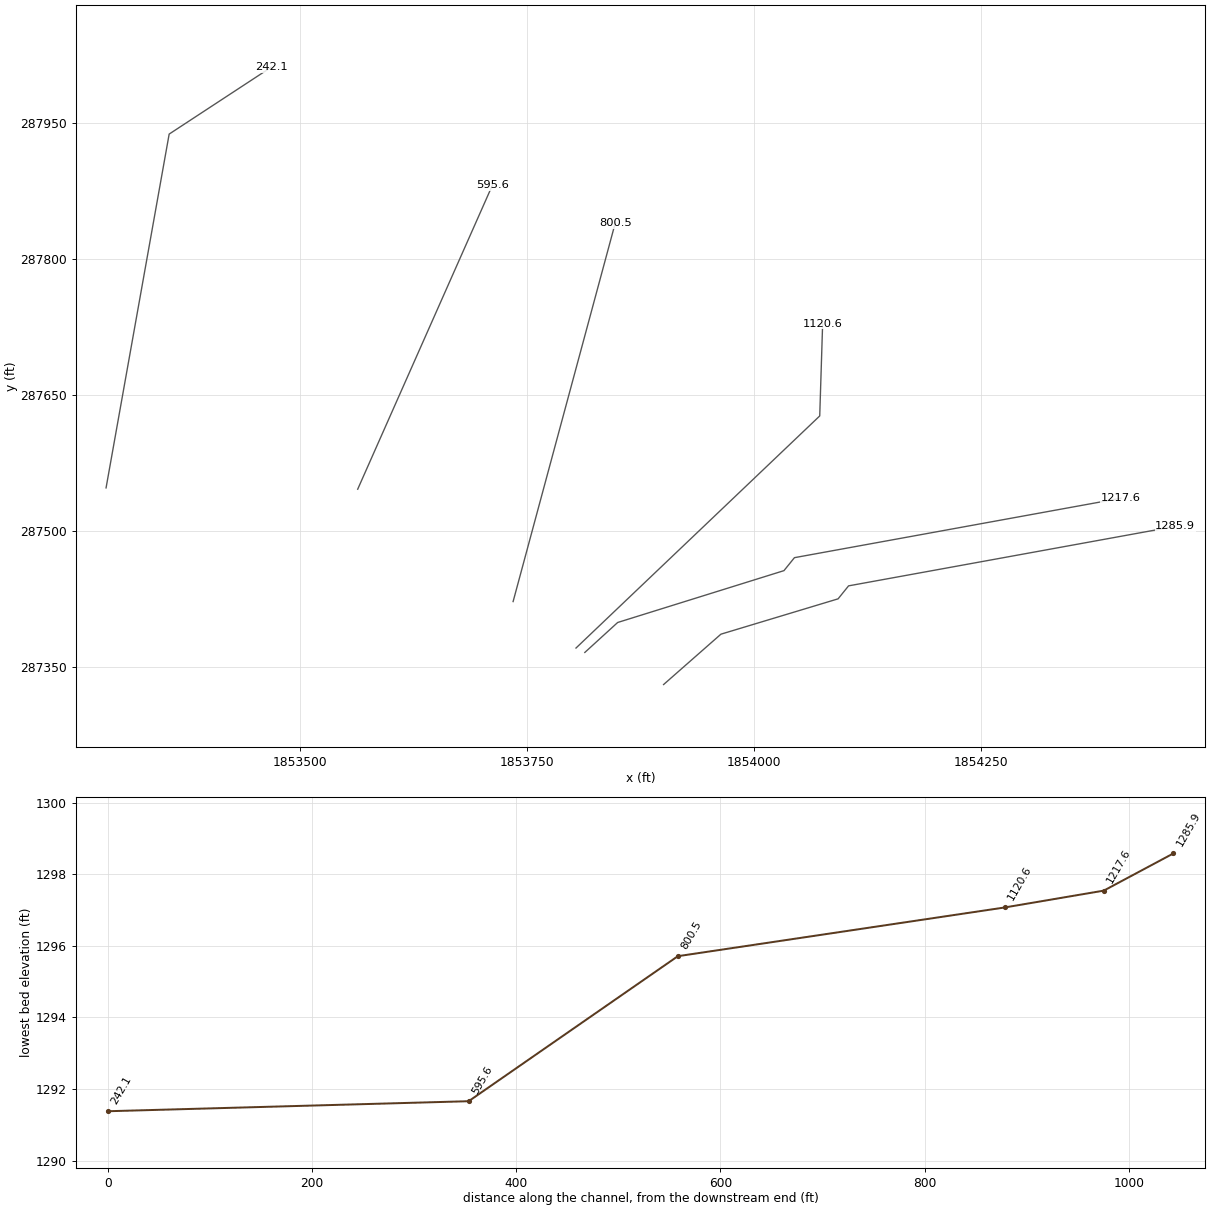
HEC-RAS study LCOVERN.prj: LCOVERN

--- LCOVERN.g01 (geometry) --- (continued)

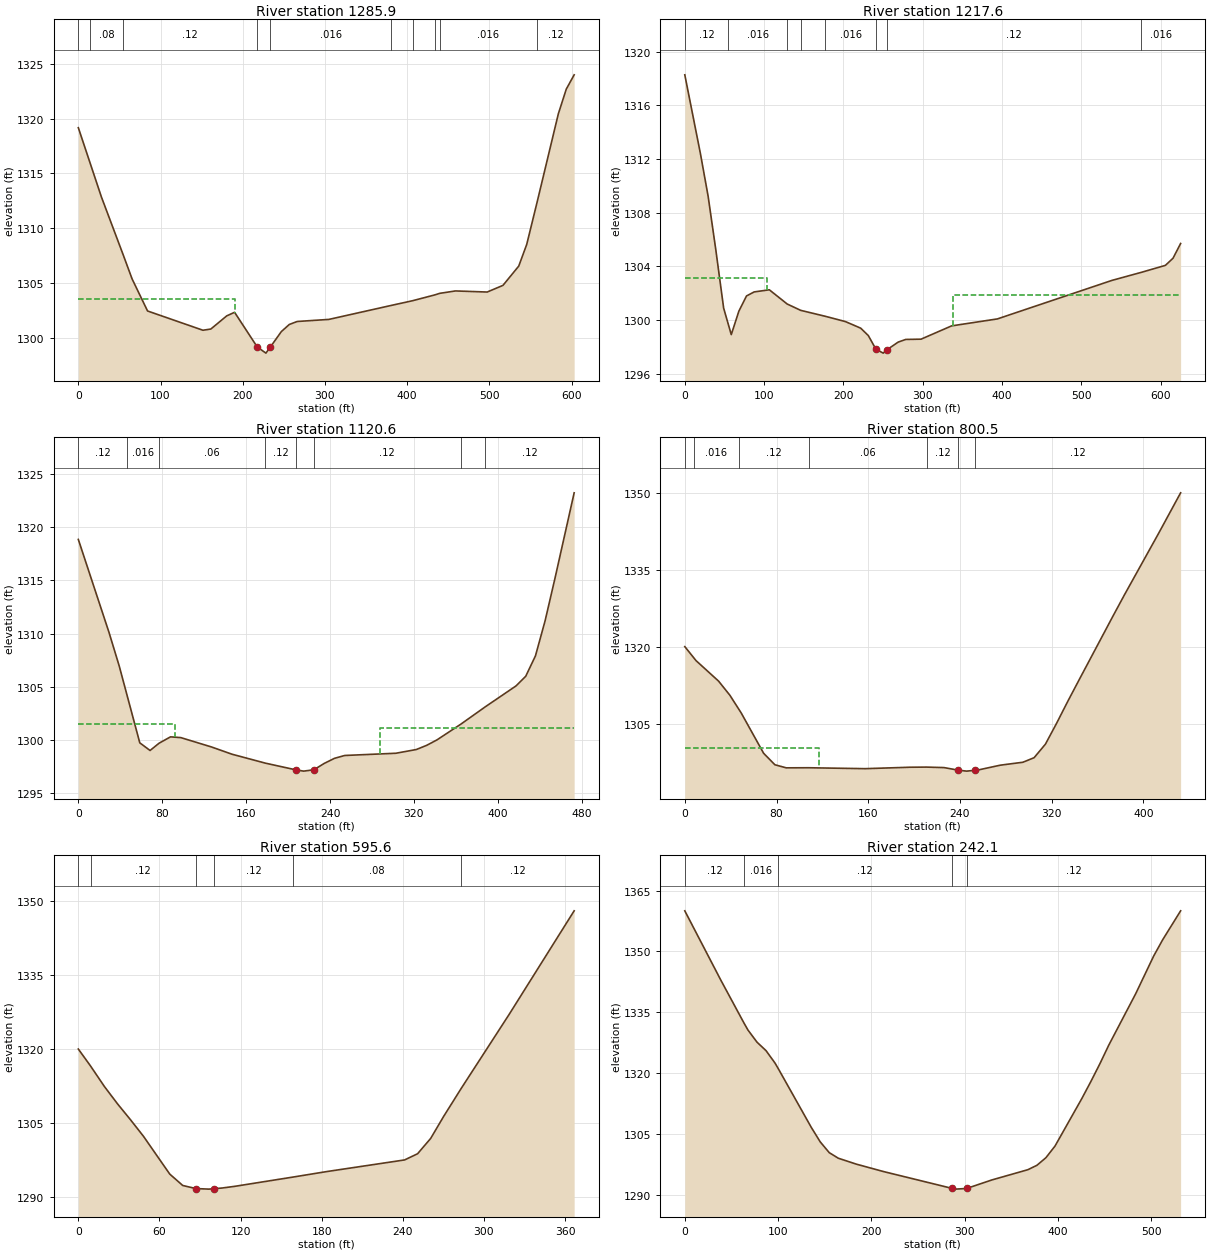
Type RM Length L Ch R = 1 ,1285.9  ,67.2,68.3,71
XS GIS Cut Line= 5
     1853900.501      287330.652     1853963.687      287386.237
     1854092.793      287425.238     1854104.339      287439.561
     1854464.227      287505.167
#Sta/Elev= 30
       0 1319.17   14.761315.847      28 1312.86   54.681307.539    65.4 1305.36
    84.2 1302.43   151.6 1300.67   161.2 1300.78   180.5 1301.98   190.1 1302.31
  217.621299.145   228.2 1298.58  233.55 1299.13     247 1300.55   256.7  1301.2
   266.3 1301.47   304.8 1301.66  380.321302.931  406.551303.365  433.631303.897
  439.61 1304.04   458.8 1304.26   497.4 1304.16   516.6 1304.77   535.8 1306.53
   545.5 1308.51  558.171312.382     584 1320.45   593.6 1322.69   603.2    1324
#Mann= 10 ,-1 , 0
       0     .12       0   14.76     .08       0   54.68     .12       0
  217.62    .045       0  233.55    .016       0  380.32     .06       0
  406.55     .12       0  433.63     .06       0  439.61    .016       0
  558.17     .12       0
#XS Ineff= 2 , 0
          190.71 1303.51
Permanent Ineff=
       F       F
Bank Sta=217.62,233.55
XS Rating Curve= 0 ,0
Exp/Cntr=0.3,0.1

Type RM Length L Ch R = 1 ,1217.6  ,88.1,97,104.2
XS GIS Cut Line= 5
     1853813.695      287366.069     1853849.889      287399.138
     1854033.137       287456.36     1854044.682      287470.683
     1854404.571       287536.29
#Sta/Elev= 30
       0 1318.28    19.6 1312.44    29.4 1309.24    39.2  1305.2      49 1300.89
   54.491299.763    58.6 1298.92    68.2 1300.67    77.8  1301.8    87.4  1302.1
   106.6 1302.26   129.1  1301.2  146.131300.728  177.241300.284   202.6 1299.89
   221.8  1299.4   231.4 1298.85     241 1297.83   250.2 1297.54   254.4 1297.77
     269 1298.36   278.6 1298.56   297.9 1298.58   336.4 1299.57   394.2 1300.09
   538.6 1302.96  575.67 1303.56     606 1304.08   615.6 1304.61   625.2 1305.71
#Mann= 8 ,-1 , 0
       0     .12       0   54.49    .016       0   129.1     .06       0
  146.13     .08       0  177.24    .016       0     241    .045       0
   254.4     .12       0  575.67    .016       0
#XS Ineff= 2 , 0
           103.3 1303.15  338.08         1301.84
Permanent Ineff=
       F       F
Bank Sta=241,254.4
XS Rating Curve= 0 ,0
Exp/Cntr=0.3,0.1

Type RM Length L Ch R = 1 ,1120.6  ,305.9,320.1,331
XS GIS Cut Line= 3
     1853803.973       287370.93     1854072.557      287627.127
     1854075.755       287728.75
#Sta/Elev= 30
       0 1318.84    29.3 1310.09    39.1 1306.91   46.371304.234    58.6 1299.73
    68.4 1299.01   77.051299.697    87.9 1300.29    97.7 1300.22     127 1299.34
   146.5 1298.66  178.321297.821  208.021297.177   214.9 1297.07   224.7  1297.2
   234.4 1297.79   244.2 1298.27     254 1298.54   302.8 1298.75   322.3  1299.1
   332.1 1299.49   341.9    1300  364.611301.473  388.031303.111   417.4 1305.08
   426.6 1305.98   435.9  1307.9   445.1  1311.2   454.4 1315.14   472.8 1323.22
#Mann= 8 ,-1 , 0
       0     .12       0   46.37    .016       0   77.05     .06       0
  178.32     .12       0  208.02    .045       0   224.7     .12       0
  364.61     .06       0  388.03     .12       0
#XS Ineff= 2 , 0
           92.36 1301.54  287.41         1301.08
Permanent Ineff=
       F       F
Bank Sta=208.02,224.7
XS Rating Curve= 0 ,0
Exp/Cntr=0.3,0.1

Type RM Length L Ch R = 1 ,800.5   ,207.7,204.9,201.2
XS GIS Cut Line= 2
     1853734.654      287422.225     1853847.181       287839.87
#Sta/Elev= 30
       0    1320    8.161317.727     9.8 1317.27    29.5 1313.26    39.3 1310.52
   47.081307.801    49.2 1307.06    68.8 1299.18    78.6 1296.95    88.5 1296.35
  107.91 1296.37   157.3 1296.19   196.6 1296.47  210.881296.495   226.1  1296.4
   238.5  1295.9   245.8 1295.71   253.5 1295.88   255.6 1295.92   275.2 1296.87
   294.9 1297.44   304.7 1298.33   314.6 1300.98   324.4 1305.08   334.2 1309.38
   344.1 1313.58   373.6    1326   383.4 1330.06   412.9 1341.93   432.5    1350
#Mann= 7 ,-1 , 0
       0     .12       0    8.16    .016       0   47.08     .12       0
  107.91     .06       0  210.88     .12       0   238.5    .045       0
   253.5     .12       0
#XS Ineff= 2 , 0
          117.13 1300.24
Permanent Ineff=
       F       F
Bank Sta=238.5,253.5
XS Rating Curve= 0 ,0
Exp/Cntr=0.3,0.1

Type RM Length L Ch R = 1 ,595.6   ,347.2,353.5,358.6
XS GIS Cut Line= 2
     1853563.405      287546.251     1853711.762      287881.617
#Sta/Elev= 22
       0 1320.02    9.031316.587    19.3 1312.43      29 1308.92    38.6  1305.7
    48.2 1302.35    67.6 1294.71    77.2  1292.4    86.8 1291.78    96.5 1291.66
  100.341291.747   106.2 1291.88   115.8 1292.23  158.781294.101   183.4  1295.2
   241.3 1297.57   250.9 1298.82   260.6 1301.93   270.2 1306.39  283.381312.136
   318.5 1326.98   366.7    1348
#Mann= 6 ,-1 , 0
       0    .016       0    9.03     .12       0    86.8    .045       0
  100.34     .12       0  158.78     .08       0  283.38     .12       0
Bank Sta=86.8,100.34
XS Rating Curve= 0 ,0
Exp/Cntr=0.3,0.1

Type RM Length L Ch R = 1 ,242.1   ,250,242.1,233.4
XS GIS Cut Line= 3
       1853286.1      287547.701     1853355.634      287938.238
     1853468.155      288012.089
#Sta/Elev= 30
       0    1360    38.7 1342.87    63.51332.302    67.7  1330.6    77.4 1327.61
    87.1 1325.51    96.8 1322.42  100.321321.023   135.4 1306.66   145.1 1303.04
   154.8 1300.37   164.5    1299   183.8 1297.54   212.8 1295.72  286.541291.557
   290.2 1291.38  302.011291.543     329 1293.64   367.6 1296.17   377.3 1297.25
     387 1299.14   396.7    1302   425.5 1313.74   435.1  1317.9   444.8  1322.3
   454.4 1326.92   483.2 1339.58   502.4 1348.84     512 1352.84   531.3    1360
#Mann= 5 ,-1 , 0
       0     .12       0    63.5    .016       0  100.32     .12       0
  286.54    .045       0  302.01     .12       0
Bank Sta=286.54,302.01
XS Rating Curve= 0 ,0
Exp/Cntr=0.3,0.1

Chan Stop Cuts=-1
Use User Specified Reach Order=0
Composite Channel Slope=5